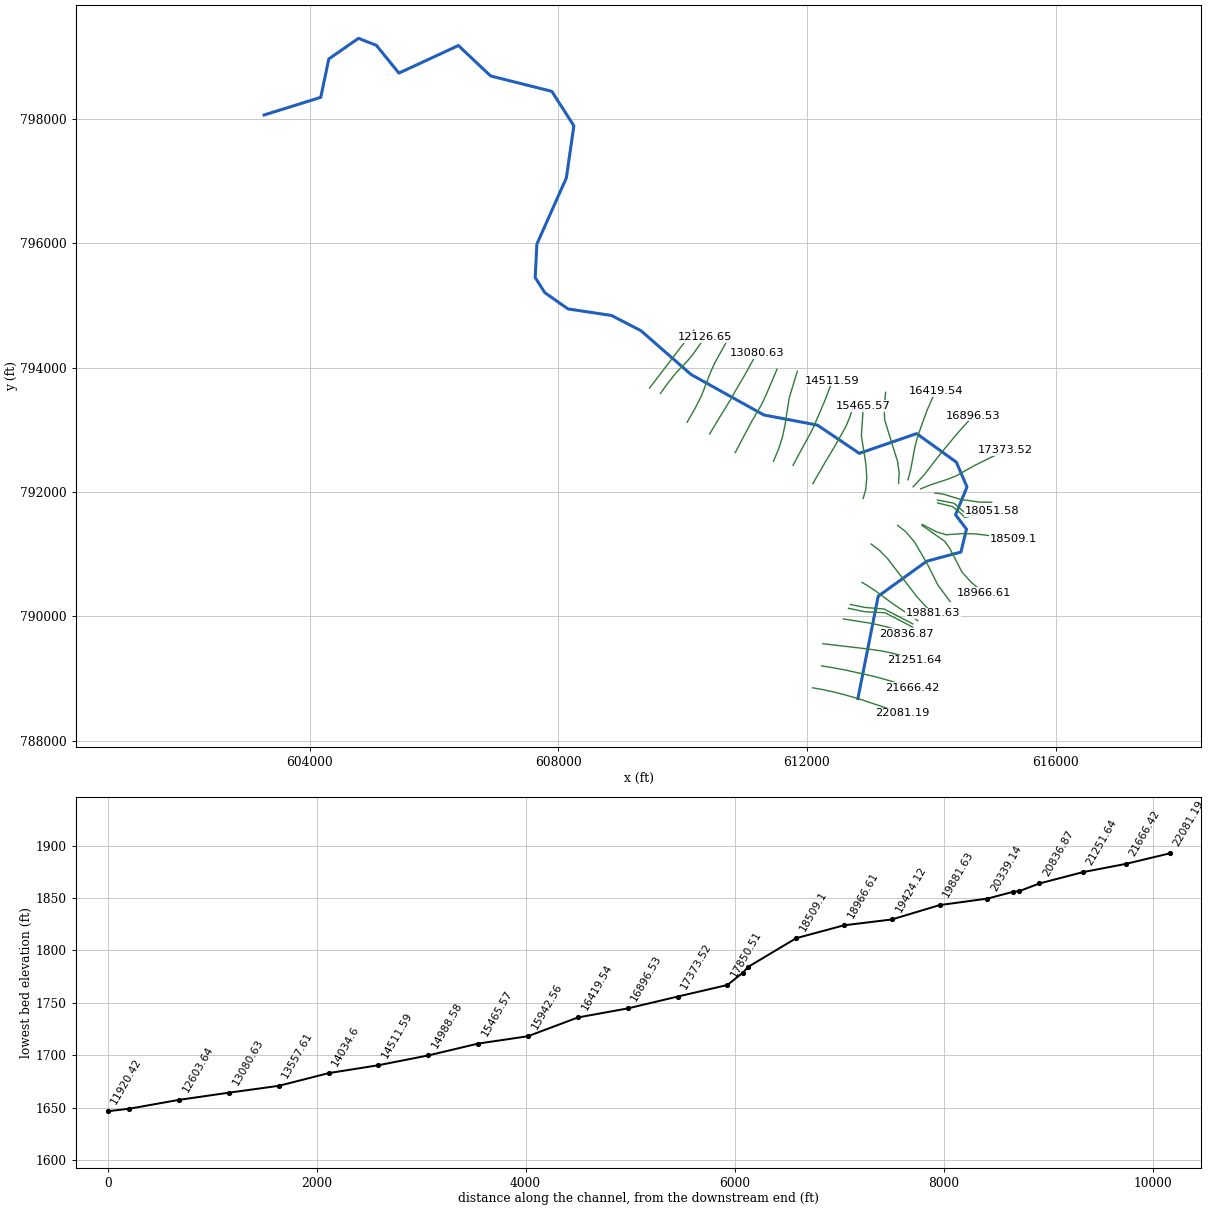
--- 10355_ras.prj (project) ---

Proj Title=10355
Current Plan=p01
Default Exp/Contr=0.3,0.1
English Units
Geom File=g01
Flow File=f01
Plan File=p01
Y Axis Title=Elevation
X Axis Title(PF)=Main Channel Distance
X Axis Title(XS)=Station
BEGIN DESCRIPTION:
RFD model 10355 exported to HEC-RAS
END DESCRIPTION:

--- 10355_ras.p01 (plan) ---

Plan Title=Plan 01
Program Version=4.10
Short Identifier=Plan 01
Geom File=g01
Flow File=f01
Subcritical Flow
Calc Critical at every XS
Secant Critical Depth

--- 10355_ras.f01 (steady flow) ---

Flow Title=Flow 01
Program Version=5.01
Number of Profiles= 6
Profile Names=10yr,25yr,50yr,100yr,100plus,500yr
River Rch & RM=10355,49,22081.19
 7646.8513746.8620328.02 29182.543796.9362195.38
River Rch & RM=10355,49,21666.42
 7820.6614007.8620663.4529596.66 44418.562778.55
River Rch & RM=10355,49,21251.64
 7834.6914028.8820690.4329629.9344468.4362825.28
River Rch & RM=10355,49,20836.87
 7864.9214074.1720748.5429701.5744575.9562925.84
River Rch & RM=10355,49,20644.03
    788014096.7620777.5129737.2744629.5362975.93
River Rch & RM=10355,49,20339.14
 7887.2614107.6220791.4429754.4444655.29   63000
River Rch & RM=10355,49,19881.63
 7898.1314123.8920812.3129780.1544693.8863036.05
River Rch & RM=10355,49,19424.12
 9181.1616019.9523223.3232727.7649117.6367101.94
River Rch & RM=10355,49,18966.61
 9190.6216033.7623240.7432748.8949149.3567130.63
River Rch & RM=10355,49, 18509.1
 9216.96 16072.223289.22 32807.749237.6167210.45
River Rch & RM=10355,49,18051.58
 9227.8716088.13 23309.332832.0649274.1767243.49
River Rch & RM=10355,49,17998.03
 9229.1116089.9423311.5832834.8249278.3267247.24
River Rch & RM=10355,49,17850.51
 9230.8516092.4723314.77 32838.749284.13 67252.5
River Rch & RM=10355,49,17373.52
  9251.916123.1823353.4932885.6449354.5967316.15
River Rch & RM=10355,49,16896.53
 9765.0116868.1524289.6734017.65 51053.568841.98
River Rch & RM=10355,49,16419.54
 9975.3417171.6724669.5434475.2351740.2469453.88
River Rch & RM=10355,49,15942.56
10034.1617256.3624775.3834602.5551931.3269623.64
River Rch & RM=10355,49,15465.57
10067.1917303.8824834.7434673.9352038.4469718.72
River Rch & RM=10355,49,14988.58
10117.97 17376.9 24925.9 34783.552202.8869864.55
River Rch & RM=10355,49,14511.59
10225.63 17531.525118.7635015.1152550.4770172.28
River Rch & RM=10355,49, 14034.6
10242.8417556.1925149.5435052.0452605.91 70221.3
River Rch & RM=10355,49,13557.61
10252.47   1757025166.75 35072.752636.91 70248.7
River Rch & RM=10355,49,13080.63
10534.8917974.1125669.6935675.3853541.4171045.85
River Rch & RM=10355,49,12603.64
10700.7518210.6325963.3736026.5454068.4371508.23
River Rch & RM=10355,49,12126.65
10712.95   1822825984.9236052.2954107.0771542.07
River Rch & RM=10355,49,11920.42
10715.6218231.7925989.6236057.91 54115.571549.45
River Rch & RM=10355,49,11828.53
10743.5218271.52 26038.936116.7654203.8371626.77
River Rch & RM=10355,49,11628.92
10748.1718278.13 26047.136126.5554218.5371639.63
River Rch & RM=10355,49,11130.79
10773.3718313.9826091.5436179.6354298.1871709.32
River Rch & RM=10355,49,10632.66
10876.1218460.0426272.5336395.6154622.3371992.54
River Rch & RM=10355,49,10134.53
10893.8718485.2526303.7436432.8454678.21 72041.3
River Rch & RM=10355,49,9636.399
10935.6418544.5426377.1436520.3654809.5672155.87
River Rch & RM=10355,49,9138.269
10942.8418554.7626389.7936535.4454832.1972175.61
River Rch & RM=10355,49,8640.138
11007.74 18646.826503.6636671.1455035.8572353.04
River Rch & RM=10355,49,8142.007
11087.0518759.1726642.5836836.5955284.1572569.05
River Rch & RM=10355,49,7643.876
   1110818788.8326679.2336880.2255349.6372625.97
River Rch & RM=10355,49,7145.745
11122.8818809.8926705.26 36911.255396.1272666.36
River Rch & RM=10355,49,6647.614
11208.8718931.5126855.4437089.8655664.2672899.12
River Rch & RM=10355,49,6149.484
11228.3718959.0626889.4537130.2955724.9472951.73
River Rch & RM=10355,49,5651.353
11245.0618982.6326918.5437164.8955776.8672996.73
River Rch & RM=10355,49,5153.222
11254.8918996.5326935.6837185.2655807.4373023.23
River Rch & RM=10355,49,4655.091
11280.9419033.3126981.06 37239.255888.3973093.38
Boundary for River Rch & Prof#=10355,49,1
Up Type= 0
Dn Type= 2
Boundary for River Rch & Prof#=10355,49,2
Up Type= 0
Dn Type= 2
Boundary for River Rch & Prof#=10355,49,2
Up Type= 0
Dn Type= 2
Boundary for River Rch & Prof#=10355,49,2
Up Type= 0
Dn Type= 2
Boundary for River Rch & Prof#=10355,49,2
Up Type= 0
Dn Type= 2
Boundary for River Rch & Prof#=10355,49,2
Up Type= 0
Dn Type= 2

--- 10355_ras.g01 (geometry) ---

Geom Title=10355
Program Version=4.10

River Reach=10355,49
Reach XY= 30
612819.788300067788676.901855052613146.367691427790323.812297106
613927.427188784790887.318521738 614477.74789995 791034.53278324
614566.316077679791403.290743947614390.621633232791633.151855081
614574.649411142792081.068521738614403.121633232792481.068521738
613764.927188784792939.401855081612842.704966575792622.040743947
612168.399411052793076.207410634 611306.59385553793239.401855081
610135.760522127793890.790743962609329.510522157794595.651855066
608857.982744336794839.401855066608156.593855441794944.957410634
607783.677188784795207.457410634607629.510522097795450.512966201
607656.593855441795987.318521738608130.204966545797050.512966186
608251.732744336797889.401855081 607896.87163347798444.957410634
606912.149410993798692.179632872606394.788299888799181.068521738
605437.843855441798738.012966201605076.038299888799183.846299529
604787.149410993799297.040743977 604310.06607765798965.790743962
604180.204966545798347.735188425603269.788299888798064.401855096

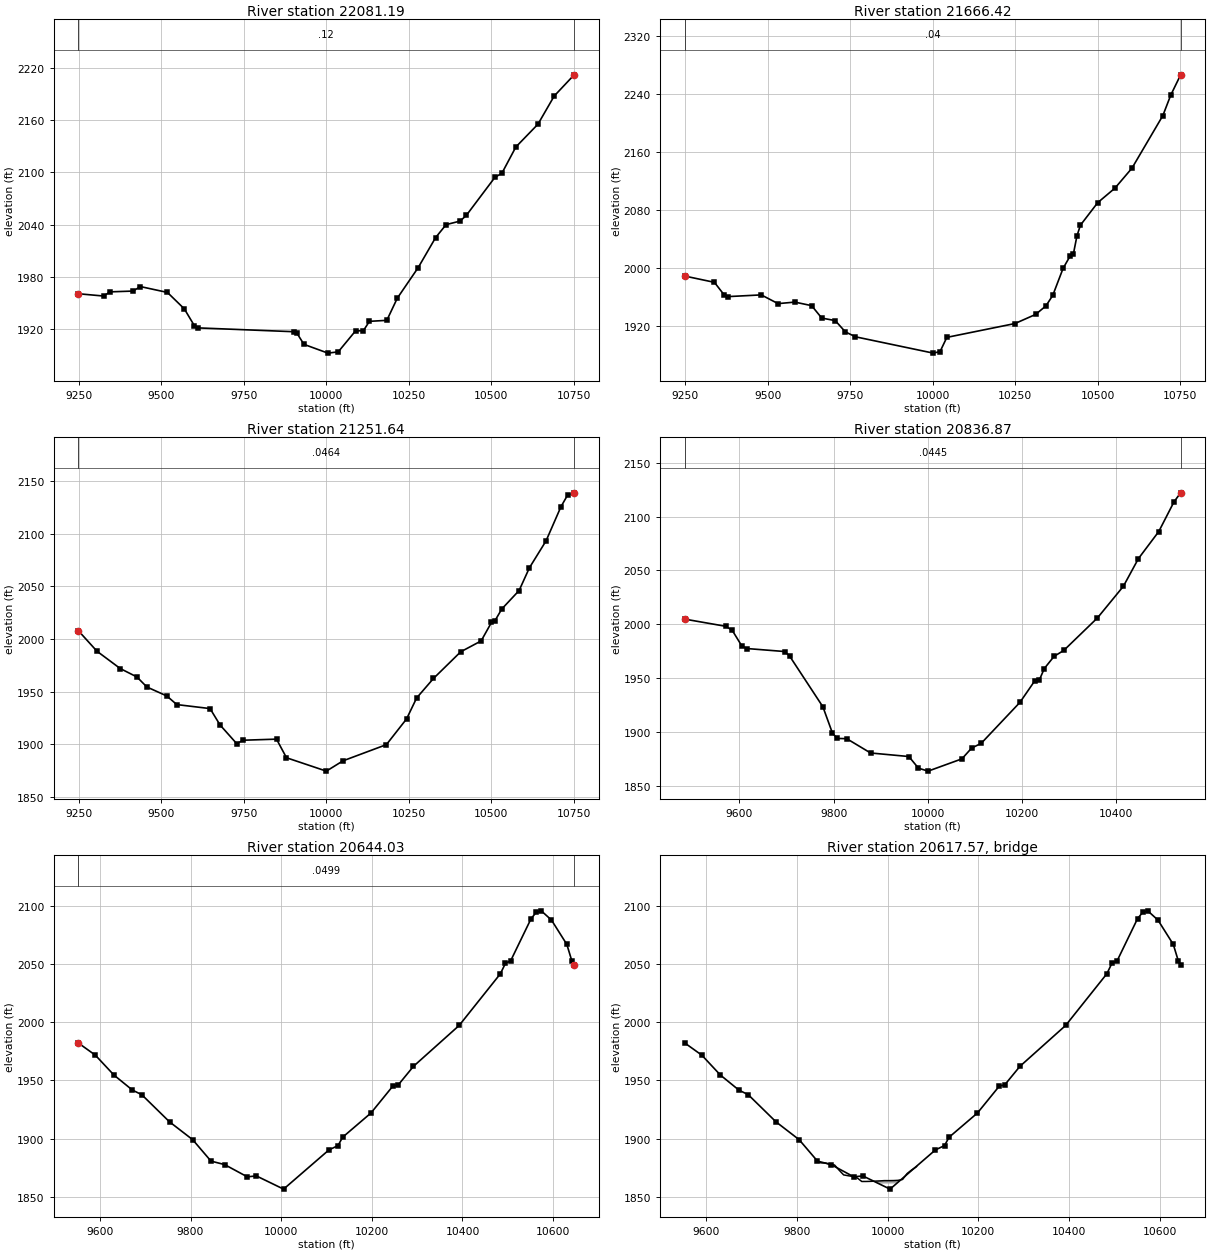
Type RM Length L Ch R = 1 ,22081.19,414.772400,414.772400,414.772400
XS GIS Cut Line= 6
612089.929330215788851.112633716612252.957537798788822.269044694
612434.068623634788783.350803407612580.688784652788745.964152748
612847.711641708788670.335119151613532.169610936788439.647749769
#Sta/Elev= 30
9249.0341960.636 9325.271958.0079345.5811962.8029414.5941963.697 9437.141968.848
9518.9661962.1269570.107 1943.27  9600.81923.796 9611.121921.4359901.1931917.058
 9911.59 1915.149932.3841902.55110005.141892.46810036.331893.93810088.791918.021
10112.361918.13510130.761928.96110183.511930.091 10215.21955.50210278.591990.669
 10331.22025.037 10363.12039.95710405.362044.02510424.242050.511   10511 2094.25
10532.13 2098.9910574.392129.08310641.34 2155.2610690.592187.59610750.992211.905
#Mann= 3 , 0 , 0
9249.034    0.12       09249.034    0.12       010750.99    0.12       0
#XS Ineff= 2 , 0
       0                               0
Bank Sta=9249.034,10750.99
Exp/Cntr=0.3,0.1

Type RM Length L Ch R = 1 ,21666.42,414.772500,414.772500,414.772500
XS GIS Cut Line= 6
612236.436996709789203.065070864612409.663647403789175.537573341
 612619.42052615789136.886938965613074.951756798789035.548579223
613351.304917415788959.354345591613693.445877916788847.738385415
#Sta/Elev= 30
9249.015 1988.849338.6891980.1939369.0661962.3789379.1911960.4819480.683 1962.87
9531.5251950.8189582.3671952.9249633.2091948.0229663.848 1930.919704.7321927.395
9735.3951911.8519766.0581905.05310001.731882.53710022.271884.72310042.811904.269
10249.181923.35910311.641935.90310342.87 1947.6310363.691962.22310394.951999.501
10415.912016.19910426.392019.90810436.882044.10610447.362058.98210499.772090.069
10552.182110.199 10603.62137.70610697.152210.20610720.952238.31510750.982266.432
#Mann= 3 , 0 , 0
9249.015    0.04       09249.015    0.04       010750.98    0.04       0
#XS Ineff= 2 , 0
       0                               0
Bank Sta=9249.015,10750.98
Exp/Cntr=0.3,0.1

Type RM Length L Ch R = 1 ,21251.64,414.772500,414.772500,414.772500
XS GIS Cut Line= 6
612258.900167299789560.329198136612990.910779587789474.080679311
613208.008707494789442.402474333613328.159621641789418.335637534
613470.630341937789382.486280871613732.896997031789296.706176853
#Sta/Elev= 30
9249.0032007.8549305.5191988.3489376.0391971.902 9426.411963.9479456.6321954.415
9517.0781945.8959547.3011937.7189648.0431933.9339678.2661918.383  9728.61900.706
9748.7231903.8939849.3391904.9299879.5241887.27110000.29 1874.5710050.74 1884.34
 10182.21899.72810243.231924.09910273.831944.02210324.821962.51710407.28 1987.81
10469.151998.13110500.442015.647 10510.92017.23110531.822028.47210584.122045.942
 10615.52067.594 10665.72093.03410710.782125.38210731.982137.04310750.952138.682
#Mann= 3 , 0 , 0
9249.003  0.0464       09249.003  0.0464       010750.95  0.0464       0
#XS Ineff= 2 , 0
       0                               0
Bank Sta=9249.003,10750.95
Exp/Cntr=0.3,0.1

Type RM Length L Ch R = 1 ,20836.87,192.846300,192.846300,192.846300
XS GIS Cut Line= 6
612585.319866103789958.566156843612979.950841356789896.581490007
613073.198237764789879.397586056613277.010639908789833.076020045
613446.640981692789783.896210136613607.933220416789721.663731148
#Sta/Elev= 30
9483.9172004.8489571.3461998.1639584.8191994.3249605.064 1979.929615.1871977.591
9696.1681974.783 9706.291970.7089777.1491923.5169797.3941899.1579807.516 1894.15
9827.7621893.9149878.3751880.6519959.6991877.3529980.0511866.55410000.561863.806
10072.351875.19610092.861885.14810113.371889.621 10195.51927.568 10226.6  1947.3
10236.961948.53610247.331959.02910268.061970.312 10288.81975.85910360.252006.036
10415.22 2035.3410447.192061.04510490.412086.17510522.822113.76710536.792122.065
#Mann= 3 , 0 , 0
9483.917  0.0445       09483.917  0.0445       010536.79  0.0445       0
#XS Ineff= 2 , 0
       0                               0
Bank Sta=9483.917,10536.79
Exp/Cntr=0.3,0.1

Type RM Length L Ch R = 1 ,20644.03,63.021900,63.021900,63.021900
XS GIS Cut Line= 4
612668.103518623790129.751906292612931.992407519790074.196350724
 613256.64518531790058.571350724613699.353518623789827.668572948
#Sta/Elev= 30
 9552.461982.2599590.1651971.7219631.0421954.6539671.919 1941.699692.3571937.797
9753.6731914.4089804.7691899.0489845.1681880.6239875.2021877.635 9925.261867.096
9945.2831867.87510005.351856.51210105.471890.27110125.491893.962 10135.51901.134
10198.131922.00910246.811945.35710258.091946.09110291.931962.17610392.751997.345
10483.662041.79910494.942050.89610506.222052.84710551.332089.15110562.612094.616
10573.892095.97110596.442088.02610630.28  2067.110641.562052.65110646.472048.977
#Mann= 3 , 0 , 0
 9552.46  0.0499       0 9552.46  0.0499       010646.47  0.0499       0
#XS Ineff= 2 , 0
       0                               0
Bank Sta=9552.46,10646.47
Exp/Cntr=0.3,0.1

Type RM Length L Ch R = 3 ,20617.57,,,
BEGIN DESCRIPTION:
END DESCRIPTION:
Bridge Culvert--1,0,-1,-1, 0
Deck Dist Width WeirC Skew NumUp NumDn MinLoCord MaxHiCord MaxSubmerge Is_Ogee
19.864000,23.293900,2.6,0, 31, 31, , , 0.95, 0, 0,0,,
 9841.18 9842.73 9849.36 9852.90 9862.90 9872.90 9882.91 9885.88 9892.91 9902.91
 9912.92 9922.92 9932.92 9942.93 9952.93 9962.93 9972.94 9980.29 9980.29 9982.94
 9992.9410002.9510012.9510018.6810018.6810022.9510032.9610042.9610052.9710062.97
10063.87
 1880.80 1880.10 1879.46 1879.12 1878.95 1877.95 1877.27 1875.96 1872.85 1868.75
 1868.04 1867.42 1866.15 1863.09 1863.10 1863.21 1863.40 1863.54 1863.54 1863.59
 1863.83 1863.82 1863.87 1863.99 1863.99 1864.07 1864.82 1869.91 1873.02 1875.62
 1875.92
  880.80  880.10  879.46  879.12  878.95  877.95  877.27  875.96  872.85  868.75
  868.04  867.42  866.15  863.09  863.10  863.21  863.40  863.54 1861.04 1861.09
 1861.33 1861.32 1861.37 1861.49  863.99  864.07  864.82  869.91  873.02  875.62
  875.92
 9841.18 9842.73 9849.36 9852.90 9862.90 9872.90 9882.91 9885.88 9892.91 9902.91
 9912.92 9922.92 9932.92 9942.93 9952.93 9962.93 9972.94 9974.79 9974.79 9982.94
 9992.9410002.9510012.9510013.1710013.1710022.9510032.9610042.9610052.9710062.97
10063.87
 1880.80 1880.10 1879.46 1879.12 1878.95 1877.95 1877.27 1875.96 1872.85 1868.75
 1868.04 1867.42 1866.15 1863.09 1863.10 1863.21 1863.40 1863.43 1863.43 1863.59
 1863.83 1863.82 1863.87 1863.87 1863.87 1864.07 1864.82 1869.91 1873.02 1875.62
 1875.92
  880.80  880.10  879.46  879.12  878.95  877.95  877.27  875.96  872.85  868.75
  868.04  867.42  866.15  863.09  863.10  863.21  863.40  863.43 1860.93 1861.09
 1861.33 1861.32 1861.37 1861.37  863.87  864.07  864.82  869.91  873.02  875.62
  875.92
BR Coef=-1 , 0 , 0 ,, 0 ,,,0.8,0,1,0,
WSPro=,,,, 1 ,,,, 0 ,,,, 0 ,,,,-1 ,-1 ,-1 , 0 , 0 , 0 , 0 , 0
BC Design=,, 0 ,, 0 ,,,,,,

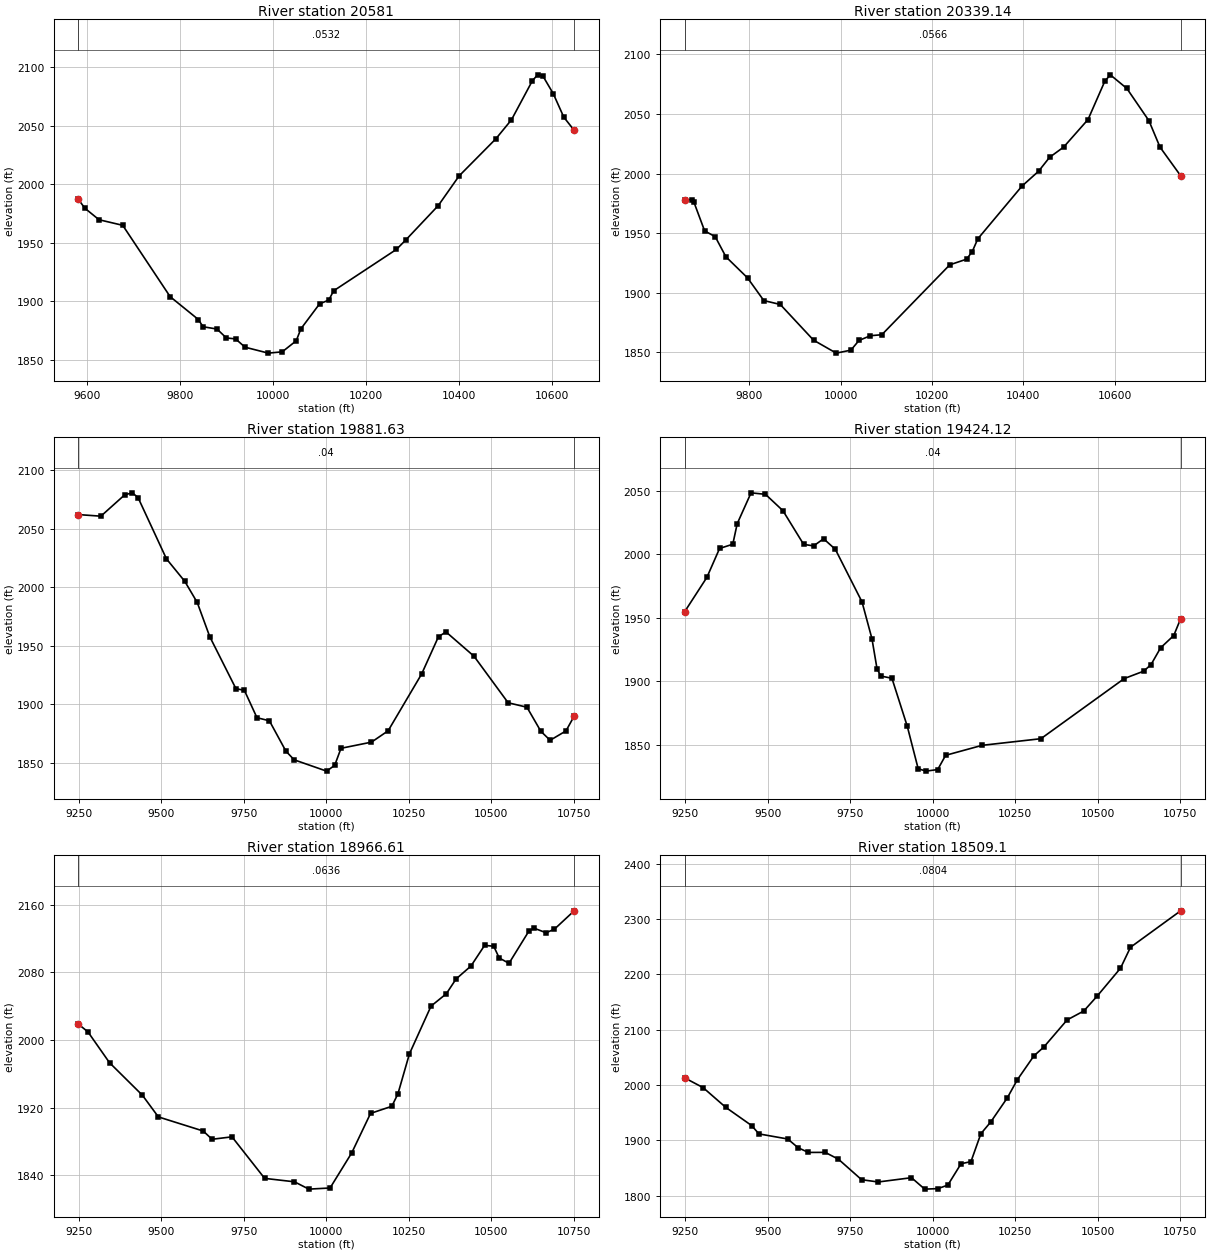
Type RM Length L Ch R = 1 ,   20581,241.858800,241.858800,241.858800
XS GIS Cut Line= 4
612701.355019271790190.736868396612928.785574824790143.861868396
613243.021685958790117.820201725 613704.82724154789878.236868396
#Sta/Elev= 30
9580.3051987.0999594.2371979.5189624.8681969.6529675.9191964.8819778.0211903.979
9838.8211884.4429848.8551878.2919878.9581876.3159899.0261868.7429919.0951867.882
9939.163 1860.859989.3351855.76410019.441856.86610049.541866.30310059.571876.501
10099.711897.75810119.781901.12910130.061908.95210265.251944.30410285.96 1952.57
10355.371981.70610400.432007.11410479.292038.66610513.092054.97510558.152088.351
10569.422093.36610580.682092.40510603.222077.18110625.75 2057.2410648.082045.983
#Mann= 3 , 0 , 0
9580.305  0.0532       09580.305  0.0532       010648.08  0.0532       0
#XS Ineff= 2 , 0
       0                               0
Bank Sta=9580.305,10648.08
Exp/Cntr=0.3,0.1

Type RM Length L Ch R = 1 ,20339.14,457.512400,457.512400,457.512400
XS GIS Cut Line= 6
612887.535439425790545.532625832612970.590090479790496.380157067
 613122.57149598790395.547226398613309.318472204790256.251574589
613414.554103505790180.909785395613782.394168309789931.016868617
#Sta/Elev= 30
9658.3841977.7649674.1011978.0629678.4681975.8989701.7741951.9229725.0791946.995
9748.3851930.1859795.7891912.4749831.4391893.4519867.4981890.1669940.328 1860.25
9990.0491849.35510022.17 1851.8610039.991860.00510064.971863.96810089.951864.796
10238.771923.42110275.66 1928.1810287.961934.54210300.251945.26210396.971989.484
10433.232001.91810457.412013.60210488.182022.17910541.572045.30210578.31 2077.38
10590.392082.79610626.662071.34710675.022044.296 10699.22022.17410744.411998.177
#Mann= 3 , 0 , 0
9658.384  0.0566       09658.384  0.0566       010744.41  0.0566       0
#XS Ineff= 2 , 0
       0                               0
Bank Sta=9658.384,10744.41
Exp/Cntr=0.3,0.1

Type RM Length L Ch R = 1 ,19881.63,457.512400,457.512400,457.512400
XS GIS Cut Line= 6
 613032.58534542791164.090633498613164.003393197791063.672948845
613294.351609224790932.169443973613759.360771597790327.537630702
613899.839405013790171.894555849614028.226271902790048.085728854
#Sta/Elev= 30
9249.0362061.9289317.3692060.5779389.6742078.8089412.5532080.4899429.8262076.491
9516.0182024.1559571.4272005.0349609.2441986.9689647.1941957.7979726.4961913.445
9751.9771912.0969790.1291888.7189827.7691886.1039877.7621860.2329902.7581852.813
 10001.11843.16210025.591848.08610044.721862.63110137.071867.88910187.421877.549
10289.021926.02610340.041957.86410362.891961.85110447.541941.16110550.941901.474
10607.97 1897.6510650.151877.10110678.271869.47310726.111877.44410750.971890.064
#Mann= 3 , 0 , 0
9249.036    0.04       09249.036    0.04       010750.97    0.04       0
#XS Ineff= 2 , 0
       0                               0
Bank Sta=9249.036,10750.97
Exp/Cntr=0.3,0.1

Type RM Length L Ch R = 1 ,19424.12,457.512300,457.512300,457.512300
XS GIS Cut Line= 6
613459.740135094 791463.21017591 613590.18851672791361.511970762
613733.409589791791193.068953203613936.270558722 790842.54671751
614108.456922647790500.420250946614303.258456276790239.356102988
#Sta/Elev= 30
 9249.071954.9869315.9921981.8379354.4242004.5669394.4242007.8959407.8042024.037
9449.7692048.319 9493.452047.137 9546.312034.2719608.9992007.782 9639.21 2006.58
9669.4562012.1879704.9612003.933  9785.91962.5069815.9961933.5089831.2521910.037
9842.5621904.252 9876.491902.473 9923.051864.6069955.9111831.3719979.5581829.447
10015.061830.66310039.081841.87710149.571849.73410327.741854.94910580.291902.265
10638.931908.04310661.241913.21510690.241926.41110730.111936.108 10750.91949.279
#Mann= 3 , 0 , 0
 9249.07    0.04       0 9249.07    0.04       0 10750.9    0.04       0
#XS Ineff= 2 , 0
       0                               0
Bank Sta=9249.07,10750.9
Exp/Cntr=0.3,0.1

Type RM Length L Ch R = 1 ,18966.61,457.512400,457.512400,457.512400
XS GIS Cut Line= 6
 613850.25107878791464.687761147614217.454813527791206.515989621
614294.173978805791101.164560297614490.672584419790718.061661126
614639.906035685790550.055896613614842.267203753790380.666977951
#Sta/Elev= 30
9249.121 2018.959278.2182009.7429343.6151973.2979443.4381934.7479491.5171909.233
9627.3011892.5679654.1931882.8019714.5271885.6789813.3821836.5899903.7671832.521
9947.273 1823.8710011.571825.215 10077.21866.74410134.161913.38610198.631921.803
10217.12 1936.56 10251.81983.65310317.432040.231 10363.72054.81910393.162072.258
10438.292087.601 10479.7 2112.0410507.242110.96110523.892097.09710553.512090.793
10614.492129.34310629.742132.28510665.752126.89810691.052131.14210750.852152.826
#Mann= 3 , 0 , 0
9249.121  0.0636       09249.121  0.0636       010750.85  0.0636       0
#XS Ineff= 2 , 0
       0                               0
Bank Sta=9249.121,10750.85
Exp/Cntr=0.3,0.1

Type RM Length L Ch R = 1 , 18509.1,457.512400,457.512400,457.512400
XS GIS Cut Line= 6
 613856.17669236791477.978831437 614093.23404527791355.385352838
614239.840000062791312.819745044614508.901577181791331.280608197
614710.720575426791326.537594363615315.319143836791252.337164478
#Sta/Elev= 30
9249.079 2012.589304.6541995.029 9372.951959.5119451.5871926.4659473.7281911.435
9560.8981902.2159592.4281886.3349623.4811877.9389674.3431878.0329714.4551865.679
9784.5921828.6179835.0491824.5249935.7611832.2689975.7711811.59510015.77 1812.51
 10045.81818.88210085.841857.49410115.871861.29410145.911911.75410175.981933.133
10226.111976.687 10256.22009.158 10306.52052.47210336.682068.499 10407.2 2117.49
10457.712133.61810498.112160.49210568.822210.94910599.132248.82110750.972314.678
#Mann= 3 , 0 , 0
9249.079  0.0804       09249.079  0.0804       010750.97  0.0804       0
#XS Ineff= 2 , 0
       0                               0
Bank Sta=9249.079,10750.97
Exp/Cntr=0.3,0.1

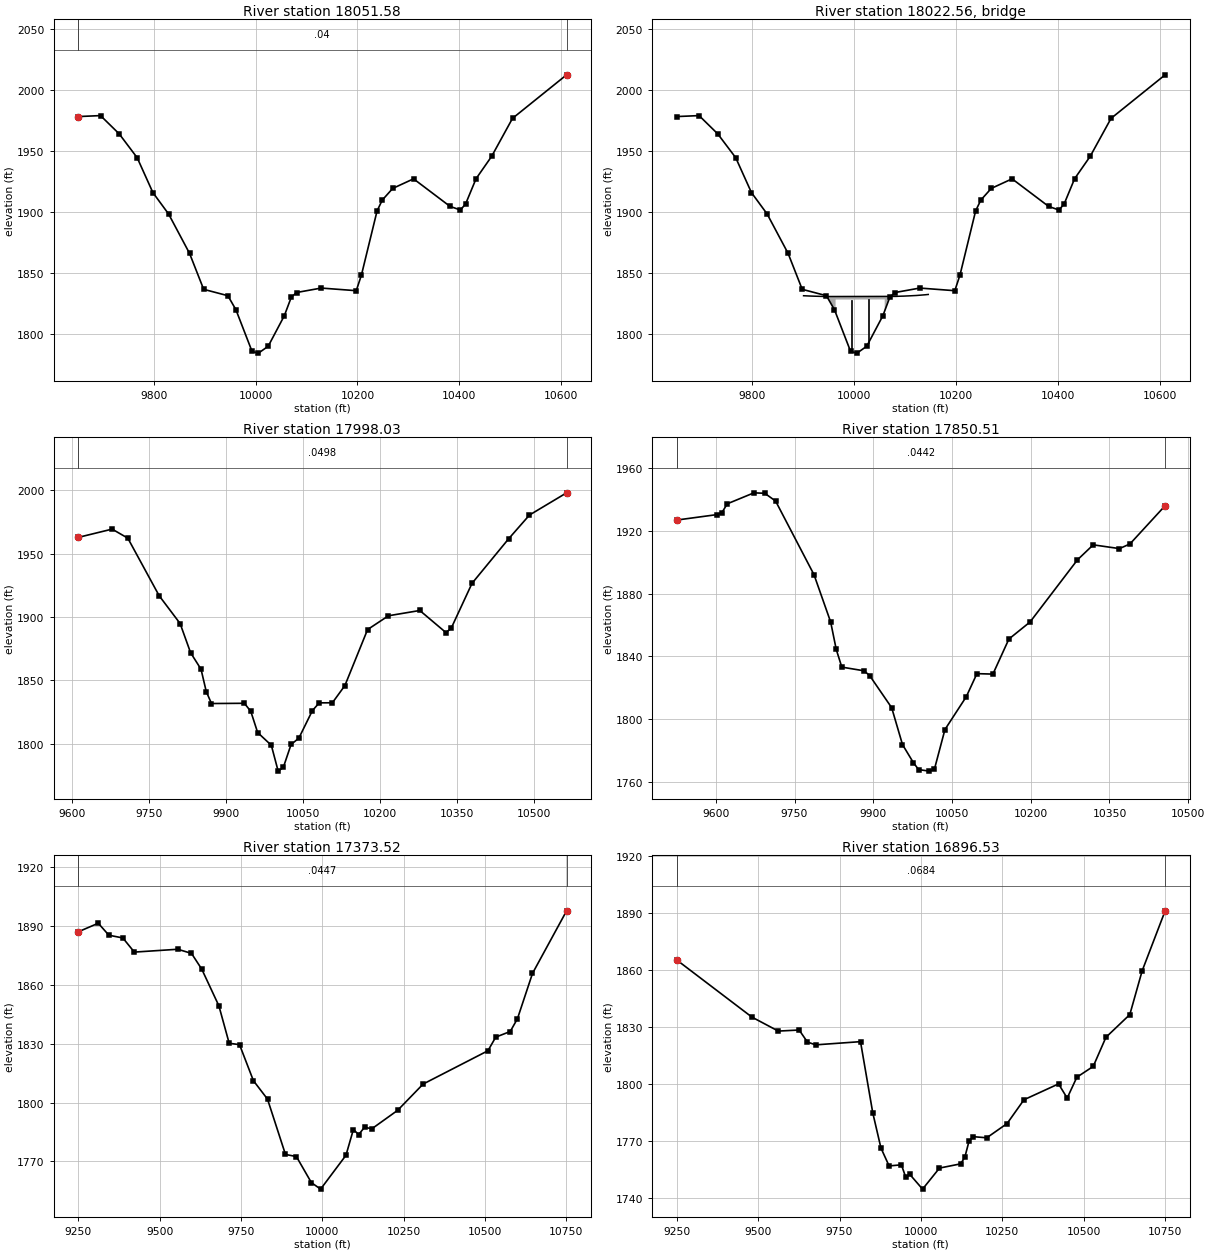
Type RM Length L Ch R = 1 ,18051.58,53.550000,53.550000,53.550000
XS GIS Cut Line= 5
614101.940165013791824.091262087614339.815029472791766.354644492
614483.021685958791649.903535068614539.006360173791591.990059391
614978.855019271791687.403535053
#Sta/Elev= 30
9650.9731978.1049695.2831978.9049731.9131963.9599767.316 1944.399798.1871915.819
9829.058 1898.279870.219    18669897.9021836.5929945.453 1831.379961.3031819.863
9993.0031785.68910005.551784.326 10024.71789.966 10056.41814.97710069.991830.062
10080.331833.97610128.88 1837.6310197.71 1835.4710207.95 1848.4110238.641900.889
10248.881909.73810269.341919.25510310.271927.101 10381.91904.55510402.361901.567
 10412.6 1906.5910433.06 1927.1910463.761945.56610504.691976.64610610.962012.306
#Mann= 3 , 0 , 0
9650.973    0.04       09650.973    0.04       010610.96    0.04       0
#XS Ineff= 2 , 0
       0                               0
Bank Sta=9650.973,10610.96
Exp/Cntr=0.3,0.1

Type RM Length L Ch R = 3 ,18022.56,,,
BEGIN DESCRIPTION:
END DESCRIPTION:
Bridge Culvert--1,0,-1,-1, 0
Deck Dist Width WeirC Skew NumUp NumDn MinLoCord MaxHiCord MaxSubmerge Is_Ogee
14.471900,24.606200,2.6,0, 24, 24, , , 0.95, 0, 0,0,,
 9900.58 9909.53 9912.56 9923.70 9926.68 9932.70 9937.85 9940.81 9944.25 9963.48
 9963.4810059.9410059.9410082.8610085.9110093.4110096.3910107.5410110.5410121.67
10124.7010135.8010138.8510145.53
 1831.34 1831.16 1831.11 1830.95 1830.91 1830.84 1830.76 1830.74 1830.70 1830.71
 1830.71 1830.79 1830.79 1830.81 1830.89 1831.00 1831.02 1831.23 1831.29 1831.53
 1831.62 1832.00 1832.10 1832.38
  831.34  831.16  831.11  830.95  830.91  830.84  830.76  830.74  830.70  830.71
 1828.21 1828.29  830.79  830.81  830.89  831.00  831.02  831.23  831.29  831.53
  831.62  832.00  832.10  832.38
 9900.58 9909.53 9912.56 9923.70 9926.68 9932.70 9937.85 9940.81 9944.25 9964.31
 9964.3110060.7710060.7710082.8610085.9110093.4110096.3910107.5410110.5410121.67
10124.7010135.8010138.8510145.53
 1831.34 1831.16 1831.11 1830.95 1830.91 1830.84 1830.76 1830.74 1830.70 1830.71
 1830.71 1830.79 1830.79 1830.81 1830.89 1831.00 1831.02 1831.23 1831.29 1831.53
 1831.62 1832.00 1832.10 1832.38
  831.34  831.16  831.11  830.95  830.91  830.84  830.76  830.74  830.70  830.71
 1828.21 1828.29  830.79  830.81  830.89  831.00  831.02  831.23  831.29  831.53
  831.62  832.00  832.10  832.38
Pier Skew, UpSta & Num, DnSta & Num=  ,9995.13, 2 ,9995.97, 2 , 0 , 0 , 0 ,,
    3.00    3.00
  830.74 1830.74
    3.00    3.00
  830.74 1830.74
Pier Skew, UpSta & Num, DnSta & Num=  ,10028.28, 2 ,10029.12, 2 , 0 , 0 , 0 ,,
    3.00    3.00
  830.77 1830.77
    3.00    3.00
  830.77 1830.77
BR Coef=-1 , 0 , 0 ,, 0 ,,,0.8,0,1,0,
WSPro=,,,, 1 ,,,, 0 ,,,, 0 ,,,,-1 ,-1 ,-1 , 0 , 0 , 0 , 0 , 0
BC Design=,, 0 ,, 0 ,,,,,,

Type RM Length L Ch R = 1 ,17998.03,147.523000,147.523000,147.523000
XS GIS Cut Line= 5
614099.688352644791870.736868382614365.796507388791820.049698845
 614526.07724151 791679.07020174614572.493598372791646.839846075
 614976.07724151791720.736868382
#Sta/Elev= 30
9612.0571962.6529678.5431969.2269709.0831962.1029770.1611916.7129810.8811894.864
 9831.241871.904  9851.61858.8619861.7791841.2619871.9591831.8529936.0191832.047
9948.4781825.6649961.7961809.0199988.4321798.96710001.751778.61110011.73 1781.47
10026.871799.59110042.011804.58410068.341826.25710081.661832.39110107.271832.439
10131.621845.993 10175.81890.11310216.461900.98510277.461905.13210328.291887.765
10338.461891.05410379.121926.54210450.291961.56210490.951980.31810563.21 1997.81
#Mann= 3 , 0 , 0
9612.057  0.0498       09612.057  0.0498       010563.21  0.0498       0
#XS Ineff= 2 , 0
       0                               0
Bank Sta=9612.057,10563.21
Exp/Cntr=0.3,0.1

Type RM Length L Ch R = 1 ,17850.51,476.988400,476.988400,476.988400
XS GIS Cut Line= 6
614059.038586835791983.320132728614201.696274766 791964.08583973
614494.913881755791874.231083729614546.981086476791871.091358834
614763.779209263791838.542613872614972.021894275791835.826446987
#Sta/Elev= 30
9525.144 1926.969601.4741930.4139611.6351931.7249621.7961937.3239672.6521944.331
 9693.281944.0329713.9081939.0789787.1011892.1229818.8291861.9499829.4321844.497
9840.0351833.2299882.4461830.8779893.049 1827.849935.0341807.3639955.651 1783.84
9976.2651772.4029986.2961767.92610006.351766.92710016.361768.01310036.511793.437
10077.131814.34710097.441829.068 10127.91828.77610158.371851.13610198.641861.994
10288.961901.61110318.991911.17610369.011908.77610389.011911.75610456.031936.145
#Mann= 3 , 0 , 0
9525.144  0.0442       09525.144  0.0442       010456.03  0.0442       0
#XS Ineff= 2 , 0
       0                               0
Bank Sta=9525.144,10456.03
Exp/Cntr=0.3,0.1

Type RM Length L Ch R = 1 ,17373.52,476.988300,476.988300,476.988300
XS GIS Cut Line= 6
 613827.60271688792050.268983359613980.940797888792112.582772341
614276.934025387792210.519823223614400.323634569792259.316018723
614686.369097301792421.596353252615190.772094239792670.882308194
#Sta/Elev= 30
9249.1021887.088 9311.451891.5259344.0381885.4169386.955 1884.029422.3481876.795
 9555.861878.2459597.9931876.1399629.5921868.0899682.2581849.3659713.8581830.273
9745.6891829.5729788.3351811.1769831.6561801.7739886.8261773.5439920.4711772.455
9966.5011759.1569994.8621755.83810072.821773.113 10095.61786.25910111.911783.684
10129.781787.39910152.571786.65410231.561796.03610309.951809.45610509.081826.446
10533.211833.406 10577.71836.27310599.951842.82610646.141865.92910750.961897.857
#Mann= 3 , 0 , 0
9249.102  0.0447       09249.102  0.0447       010750.96  0.0447       0
#XS Ineff= 2 , 0
       0                               0
Bank Sta=9249.102,10750.96
Exp/Cntr=0.3,0.1

Type RM Length L Ch R = 1 ,16896.53,476.988400,476.988400,476.988400
XS GIS Cut Line= 6
613707.722393937792082.588968834613888.177196963792279.237656254
614143.357168789 792609.91165652614392.036455844792909.835220247
614521.211217283793057.324928606614679.042421974793226.776862515
#Sta/Elev= 30
9249.0291865.3979480.5761835.237 9561.89 1827.859626.0261828.408 9651.351822.086
9676.4611820.593 9814.571822.2829852.2361784.7899877.3471766.2749902.458 1756.81
9940.3451757.3939953.3361750.9469966.327  1752.310005.331744.58910057.281755.675
10122.231757.90410135.221761.39110148.211769.913 10161.21772.22510202.631771.633
10265.111779.13810317.061791.67610423.261800.02210449.851792.56110479.621803.553
10529.891809.24610568.981824.57810642.341836.54910680.221859.55710750.971891.204
#Mann= 3 , 0 , 0
9249.029  0.0684       09249.029  0.0684       010750.97  0.0684       0
#XS Ineff= 2 , 0
       0                               0
Bank Sta=9249.029,10750.97
Exp/Cntr=0.3,0.1

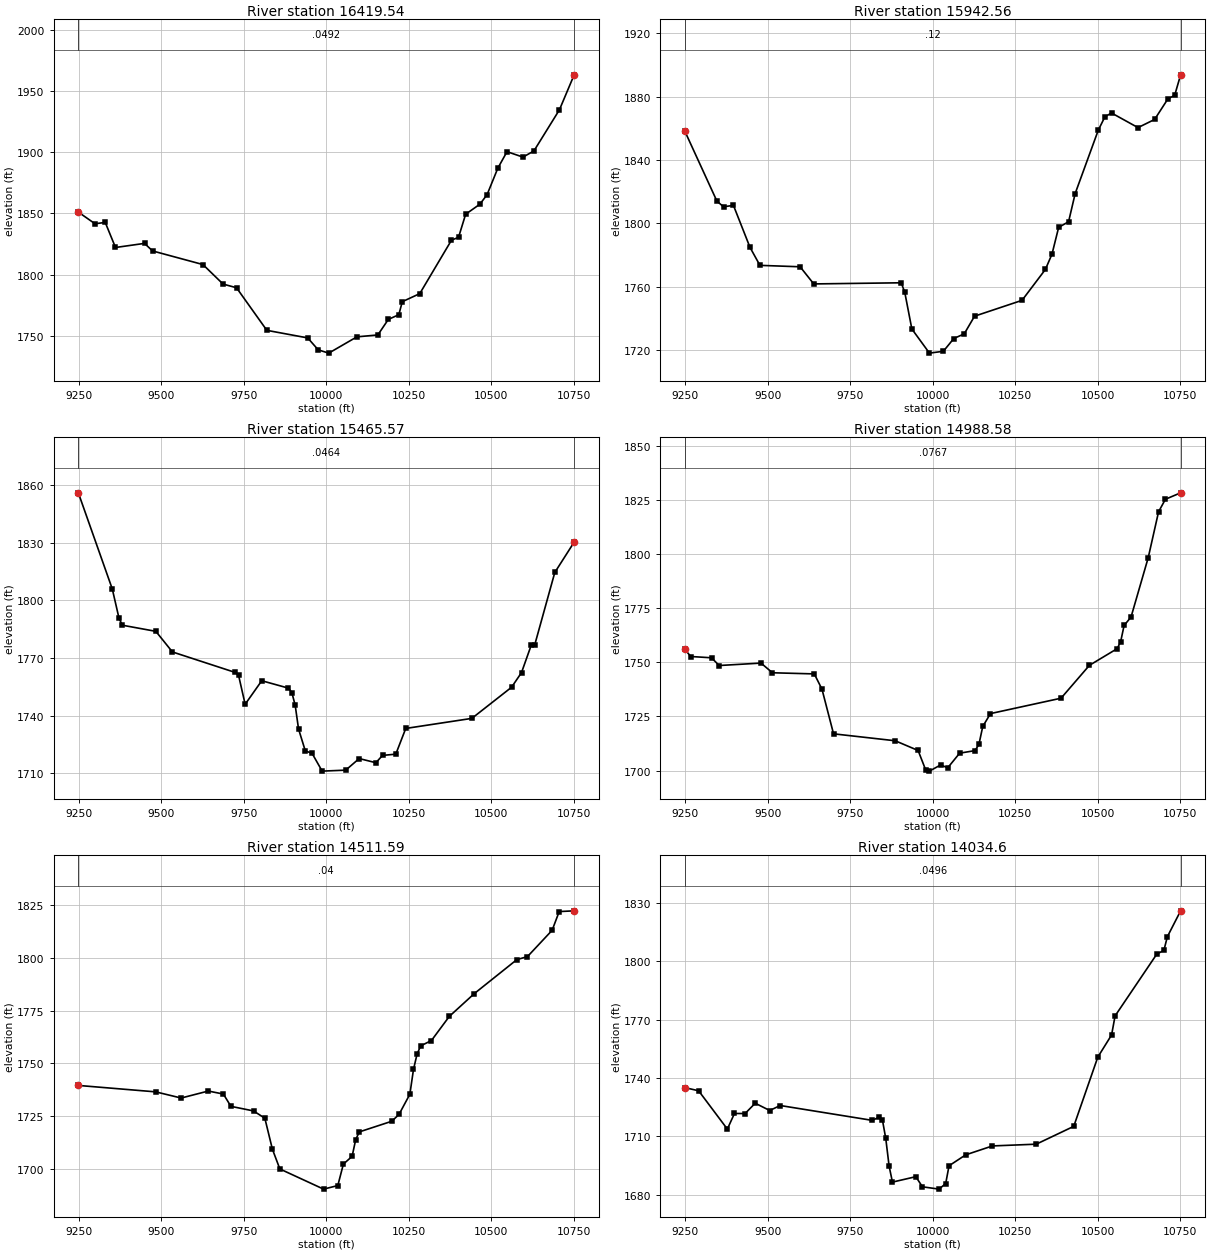
Type RM Length L Ch R = 1 ,16419.54,476.988400,476.988400,476.988400
XS GIS Cut Line= 6
 613625.07017508792197.068908861613668.653958107792356.672310215
 613733.96262923 792709.77178742 613776.30807107792880.831798458
613933.444932727793317.440799643614070.151140278793625.287876793
#Sta/Elev= 30
9249.0541851.025 9299.481841.5059330.573 1842.589361.6111822.1279449.5151825.478
9473.9391819.3129626.4831808.2079687.5011792.2669728.1791789.2799820.077 1754.53
9943.9321748.3359975.6681738.59710007.621735.93310092.781749.21210156.281750.764
10188.031763.44710219.78 1767.2610230.371777.91310283.291784.47710379.381828.093
10400.75 1830.4410422.241849.255 10465.61857.49410487.281865.295 10519.81886.878
10547.571900.31810595.871895.88310629.041900.88710706.421934.53110750.961963.018
#Mann= 3 , 0 , 0
9249.054  0.0492       09249.054  0.0492       010750.96  0.0492       0
#XS Ineff= 2 , 0
       0                               0
Bank Sta=9249.054,10750.96
Exp/Cntr=0.3,0.1

Type RM Length L Ch R = 1 ,15942.56,476.988300,476.988300,476.988300
XS GIS Cut Line= 6
613473.834906883792138.322136571613484.342843365792303.206759108
613458.934630922792486.471654053 613251.41117234793158.099293607
613241.171238842793373.413712865613266.016614521 793602.85633969
#Sta/Elev= 30
9249.049 1858.249346.3861813.9969366.4081810.4719396.4091811.3279446.492 1784.84
9476.6141773.4729598.3611772.571 9639.661761.7499904.6581762.4659915.3681756.419
9936.7871733.3039990.0861718.05610032.251719.22410063.831727.28410095.411730.218
10126.741741.38210270.531751.38410341.241770.88610361.331780.59210381.431797.465
10411.511801.00810431.521818.83310501.541858.86610521.541867.24710541.591869.679
10621.791860.44110672.12 1865.5910712.591878.65410732.831880.787 10750.91893.766
#Mann= 3 , 0 , 0
9249.049    0.12       09249.049    0.12       0 10750.9    0.12       0
#XS Ineff= 2 , 0
       0                               0
Bank Sta=9249.049,10750.9
Exp/Cntr=0.3,0.1

Type RM Length L Ch R = 1 ,15465.57,476.988400,476.988400,476.988400
XS GIS Cut Line= 6
612904.674095252791897.078887978612945.964608088792040.845512334
612963.063937445792230.088903205612948.902712148792448.139026393
612875.863038259792907.561666481612907.674484365793383.064803976
#Sta/Elev= 30
9249.0531856.0299351.9611805.8969372.4421790.5639382.6821787.0419483.8651783.856
9533.9941773.1269724.1861762.4469734.2171761.1049754.3111745.8469804.6321758.123
9885.6491754.2589895.7781751.9769905.9081745.3479916.1011732.9659936.5341721.579
9956.967 1720.329987.6171711.02410059.021711.53410099.811717.57310150.31 1715.41
10170.48 1719.21 10210.71719.869 10240.81733.26410440.991738.50310561.331754.728
10591.471762.36810621.621776.99610631.661776.91610692.261814.52410750.931830.355
#Mann= 3 , 0 , 0
9249.053  0.0464       09249.053  0.0464       010750.93  0.0464       0
#XS Ineff= 2 , 0
       0                               0
Bank Sta=9249.053,10750.93
Exp/Cntr=0.3,0.1

Type RM Length L Ch R = 1 ,14988.58,476.988400,476.988400,476.988400
XS GIS Cut Line= 6
612095.956117565792134.719406965612295.059278351792481.903031073
612438.990258524792720.669422021612622.761853105793044.972345299
  612689.9931966793204.670080299612770.828001771793469.259846633
#Sta/Elev= 30
9249.0191755.9879267.1991752.7029330.0371752.1049353.0921748.5359479.897 1749.66
 9514.481745.1859641.2851744.6599664.5351737.6019699.564 1716.979886.3861713.762
 9955.761709.267 9978.551700.3229989.9451699.73210024.041702.59610045.381701.254
10081.56 1708.0310128.261709.21510139.931712.08610151.61 1720.3810174.96 1726.32
10388.721733.43210474.571748.612 10558.71756.32610569.221759.52610579.731767.041
10600.761770.95610652.881798.42810684.091819.57410704.891825.37210750.931828.338
#Mann= 3 , 0 , 0
9249.019  0.0767       09249.019  0.0767       010750.93  0.0767       0
#XS Ineff= 2 , 0
       0                               0
Bank Sta=9249.019,10750.93
Exp/Cntr=0.3,0.1

Type RM Length L Ch R = 1 ,14511.59,476.988300,476.988300,476.988300
XS GIS Cut Line= 6
611776.195018231792428.158988624 611922.62996564792703.111372328
612060.172078387792952.247150247612100.207582641 793031.30682609
612287.913425204793470.095289644612409.728727896793787.451600777
#Sta/Elev= 30
9249.0321739.5549483.3791736.5069560.5481733.5799642.6641736.8939688.3551735.475
9711.2011729.6439779.7371727.4619814.0051724.0049836.8511709.3449859.4241699.955
9991.9341690.38810035.051692.07910051.921702.25610078.341705.92910089.281713.896
10100.211717.52310198.651722.57410220.521725.84110253.341735.39410264.271747.142
10275.211754.45810286.121758.31610318.681760.85210372.951772.31210448.591783.112
10577.461799.214 10609.5 1800.6310684.28 1813.1210705.64 1821.9910750.991822.344
#Mann= 3 , 0 , 0
9249.032    0.04       09249.032    0.04       010750.99    0.04       0
#XS Ineff= 2 , 0
       0                               0
Bank Sta=9249.032,10750.99
Exp/Cntr=0.3,0.1

Type RM Length L Ch R = 1 , 14034.6,476.988400,476.988400,476.988400
XS GIS Cut Line= 6
611463.086103723792496.649594405 611546.95330284792698.566248101
611607.776958045792890.491547182611644.895050395793062.473357812
611714.836127809 793512.63025339611846.135358088 793942.82662244
#Sta/Elev= 30
9249.0521735.0559290.9441733.4229377.9651713.7119399.4511721.7459431.6781721.713
9462.3911727.0289506.2831723.2759538.0221725.8459817.1231718.1969837.497 1719.85
9847.6671718.4199857.7851708.9039867.9021694.718 9878.021686.4419948.7991689.232
9968.9341684.02610019.251682.83310039.371685.71810049.45 1694.8510099.941700.468
10180.961705.05410313.631705.95410427.221715.12310500.111750.73210541.881762.158
 10552.41771.926   106791803.78310700.221805.62210710.831812.67810750.971825.988
#Mann= 3 , 0 , 0
9249.052  0.0496       09249.052  0.0496       010750.97  0.0496       0
#XS Ineff= 2 , 0
       0                               0
Bank Sta=9249.052,10750.97
Exp/Cntr=0.3,0.1

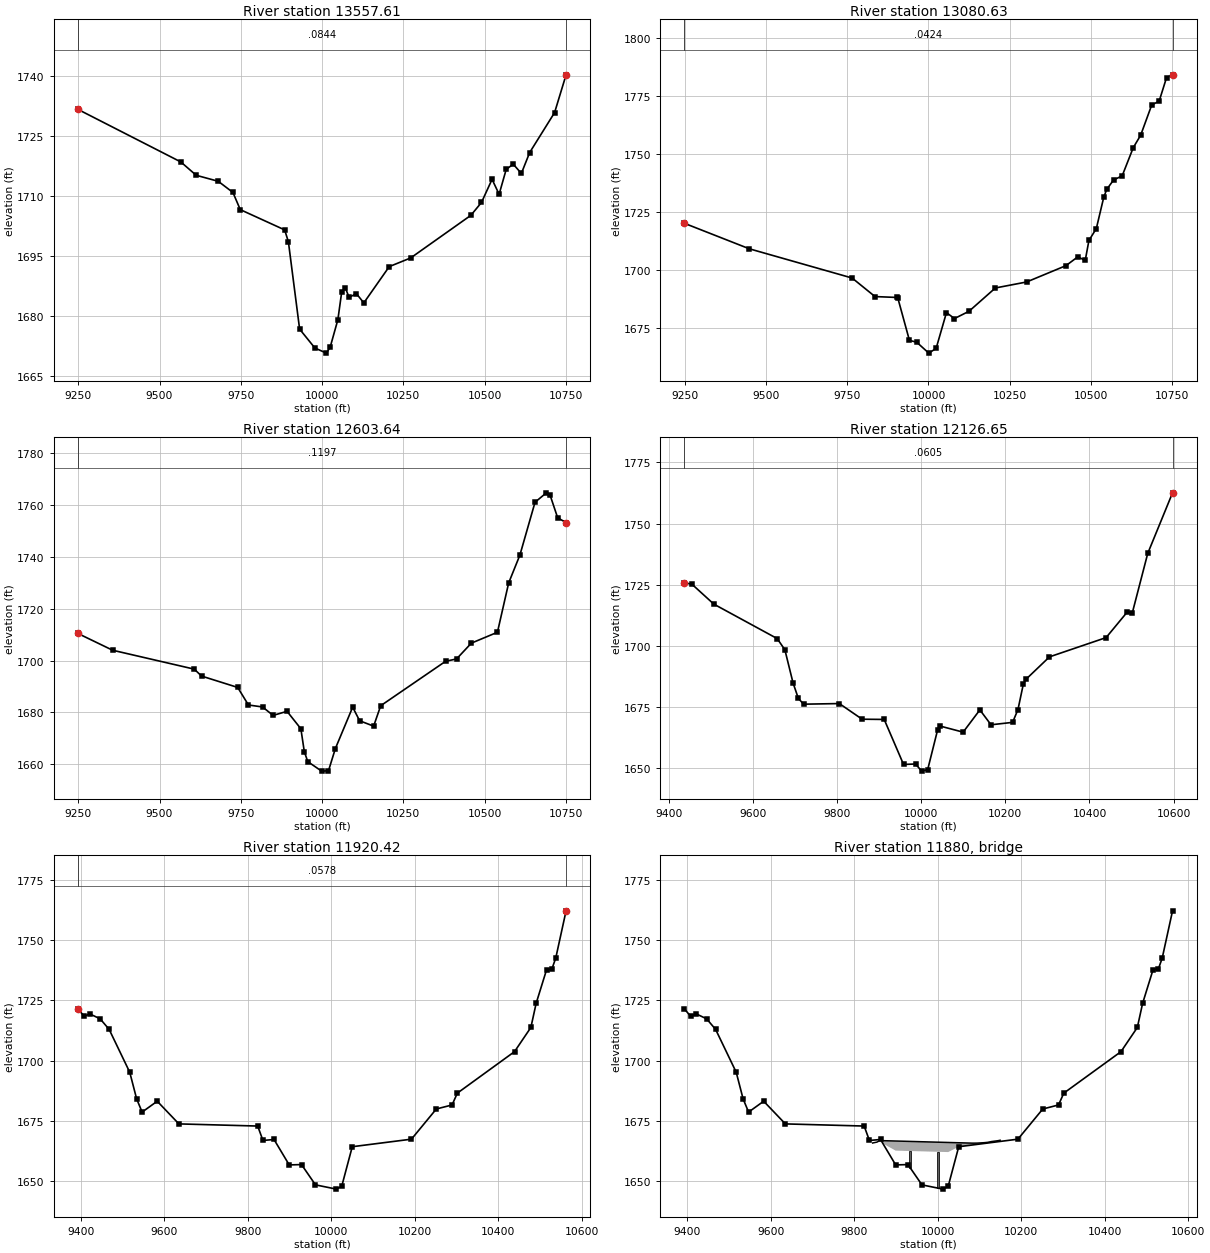
Type RM Length L Ch R = 1 ,13557.61,476.988400,476.988400,476.988400
XS GIS Cut Line= 6
610846.266809397792633.670920157611114.824636197793141.116681881
611236.218685829793344.788991189611280.838024605793428.148975417
611354.322489558793587.453908291611518.809896764793974.602184766
#Sta/Elev= 30
9249.0231731.6319565.4891718.5019612.929 1715.169680.7031713.6639725.8861710.873
9748.477 1706.589885.1071701.5169896.603 1698.529931.0921676.7249978.0511672.005
10013.481670.72410025.25 1672.25 10048.81679.08510060.561685.983 10071.91687.013
10083.251684.66910105.931685.57510128.621683.27810206.861692.34110272.841694.509
10458.041705.15810490.631708.36810523.231714.15310544.961710.41410566.691716.624
10588.421717.94410613.361715.62110638.93 1720.8410715.651730.83510750.971740.265
#Mann= 3 , 0 , 0
9249.023  0.0844       09249.023  0.0844       010750.97  0.0844       0
#XS Ineff= 2 , 0
       0                               0
Bank Sta=9249.023,10750.97
Exp/Cntr=0.3,0.1

Type RM Length L Ch R = 1 ,13080.63,476.988300,476.988300,476.988300
XS GIS Cut Line= 6
610435.381476764792933.834331837610596.526451007793201.711877393
610788.085393681793513.090479743610862.396938002793646.561385993
611043.438632026793957.850269261611191.457029845794231.255152819
#Sta/Elev= 30
9249.0131720.1249448.7621709.1379765.079 1696.549835.5241688.5459902.2351688.173
9905.9691687.7779941.3851669.671 9963.761668.885   100011664.17410023.551666.217
10055.311681.63610079.971679.07310124.58  1682.210205.811692.25410301.931694.836
10423.051701.87610459.591705.68510482.331704.121 10493.71712.73510516.451717.838
10539.191731.27810548.391734.71410569.391738.76910596.051740.59410630.161752.745
 10652.91758.08710687.021771.14910709.761772.751 10732.51782.90510750.991784.116
#Mann= 3 , 0 , 0
9249.013  0.0424       09249.013  0.0424       010750.99  0.0424       0
#XS Ineff= 2 , 0
       0                               0
Bank Sta=9249.013,10750.99
Exp/Cntr=0.3,0.1

Type RM Length L Ch R = 1 ,12603.64,476.988400,476.988400,476.988400
XS GIS Cut Line= 6
610073.620578121793122.874798916610209.365171967793360.334601372
610302.180263456793542.908561283610451.089887749 793928.48029016
610516.422787477794074.489194586610735.943262357794467.277316765
#Sta/Elev= 30
9249.0271710.4519355.8181703.9869606.8841696.6949629.4711694.0199740.6561689.636
9773.5581682.8689817.0961682.1039849.5261678.8519892.4231680.4279934.953  1673.7
9945.5851664.8359956.2181661.0289998.7481657.35610019.951657.49810041.151666.082
10094.361682.03210115.771676.78210158.861674.717 10180.61682.58310380.12 1699.71
10414.011700.63610459.551706.72810539.791710.92310574.281729.926   106091740.733
10655.451761.07110690.281764.70710701.891763.77510725.111755.07110750.981753.233
#Mann= 3 , 0 , 0
9249.027  0.1197       09249.027  0.1197       010750.98  0.1197       0
#XS Ineff= 2 , 0
       0                               0
Bank Sta=9249.027,10750.98
Exp/Cntr=0.3,0.1

Type RM Length L Ch R = 1 ,12126.65,206.232100,206.232100,206.232100
XS GIS Cut Line= 6
609645.012421068793586.125395054609744.937228297793726.887810744
609899.521080029 793923.13603836610065.099271144794092.695976047
610162.472721856794209.732973845610365.049840162794493.446559097
#Sta/Elev= 30
9436.9781725.7459454.574 1725.289506.7891717.1139657.4841703.0279675.8041698.459
9695.1691684.9699707.7311678.6299720.2931676.2249805.3091676.4789859.4781670.087
9911.9751669.9919957.9331651.6089986.5621651.79110000.911648.87710015.331649.498
   100391665.77210044.171667.31710099.611664.795 10139.41673.89410165.93 1667.81
10217.221668.79510230.011674.04910242.791684.47610248.841686.356 10304.91695.556
10439.561703.42810489.811713.87610501.991713.625 10538.5 1737.8110597.481762.565
#Mann= 3 , 0 , 0
9436.978  0.0605       09436.978  0.0605       010597.48  0.0605       0
#XS Ineff= 2 , 0
       0                               0
Bank Sta=9436.978,10597.48
Exp/Cntr=0.3,0.1

Type RM Length L Ch R = 1 ,11920.42,91.887800,91.887800,91.887800
XS GIS Cut Line= 2
609469.616593361793672.844507292610180.033260018794602.011173964
#Sta/Elev= 30
9392.8491721.476 9408.151718.3619420.7381719.4579445.9141717.3879467.5681712.985
 9516.961695.1369533.4241684.0819546.6181678.5529582.8161683.0759634.7341673.637
9823.5531672.7429836.1411666.7419862.7051667.1449899.0811656.5669928.5611656.703
9962.0211648.26110012.371646.48810024.961647.70610050.14 1664.1410191.991667.282
10251.541679.84210289.311681.522 10301.91686.43810438.951703.71310478.131713.781
10490.721723.78810515.891737.88910528.481738.11410537.731742.64710562.481762.321
#Mann= 3 , 0 , 0
9392.849  0.0578       09392.849  0.0578       010562.48  0.0578       0
#XS Ineff= 2 , 0
       0                               0
Bank Sta=9392.849,10562.48
Exp/Cntr=0.3,0.1

Type RM Length L Ch R = 3 ,   11880,,,
BEGIN DESCRIPTION:
END DESCRIPTION:
Bridge Culvert--1,0,-1,-1, 0
Deck Dist Width WeirC Skew NumUp NumDn MinLoCord MaxHiCord MaxSubmerge Is_Ogee
29.867800,32.152200,2.6,0, 20, 20, , , 0.95, 0, 0,0,,
 9843.77 9851.13 9854.00 9861.20 9868.54 9868.5410066.3810066.3810079.1510082.14
10094.5710095.7310107.0010112.5710119.4310129.4110131.8510144.2810146.2610149.33
 1665.68 1665.95 1666.05 1666.70 1666.66 1666.66 1665.71 1665.71 1665.65 1665.62
 1665.64 1665.66 1665.77 1665.84 1665.96 1666.31 1666.36 1666.65 1666.72 1666.84
  665.68  665.95  666.05  666.70  666.66 1662.66 1661.71  665.71  665.65  665.62
  665.64  665.66  665.77  665.84  665.96  666.31  666.36  666.65  666.72  666.84
 9843.77 9851.13 9854.00 9861.20 9869.02 9869.0210066.8610066.8610079.1510082.14
10094.5710095.7310107.0010112.5710119.4310129.4110131.8510144.2810146.2610149.33
 1665.68 1665.95 1666.05 1666.70 1666.66 1666.66 1665.71 1665.71 1665.65 1665.62
 1665.64 1665.66 1665.77 1665.84 1665.96 1666.31 1666.36 1666.65 1666.72 1666.84
  665.68  665.95  666.05  666.70  666.66 1662.66 1661.71  665.71  665.65  665.62
  665.64  665.66  665.77  665.84  665.96  666.31  666.36  666.65  666.72  666.84
Pier Skew, UpSta & Num, DnSta & Num=  ,9933.82, 2 ,9934.30, 2 , 0 , 0 , 0 ,,
    4.00    4.00
  666.35 1666.35
    4.00    4.00
  666.35 1666.35
Pier Skew, UpSta & Num, DnSta & Num=  ,10001.10, 2 ,10001.58, 2 , 0 , 0 , 0 ,,
    4.00    4.00
  666.03 1666.03
    4.00    4.00
  666.03 1666.03
BR Coef=-1 , 0 , 0 ,, 0 ,,,0.8,0,1,0,
WSPro=,,,, 1 ,,,, 0 ,,,, 0 ,,,,-1 ,-1 ,-1 , 0 , 0 , 0 , 0 , 0
BC Design=,, 0 ,, 0 ,,,,,,