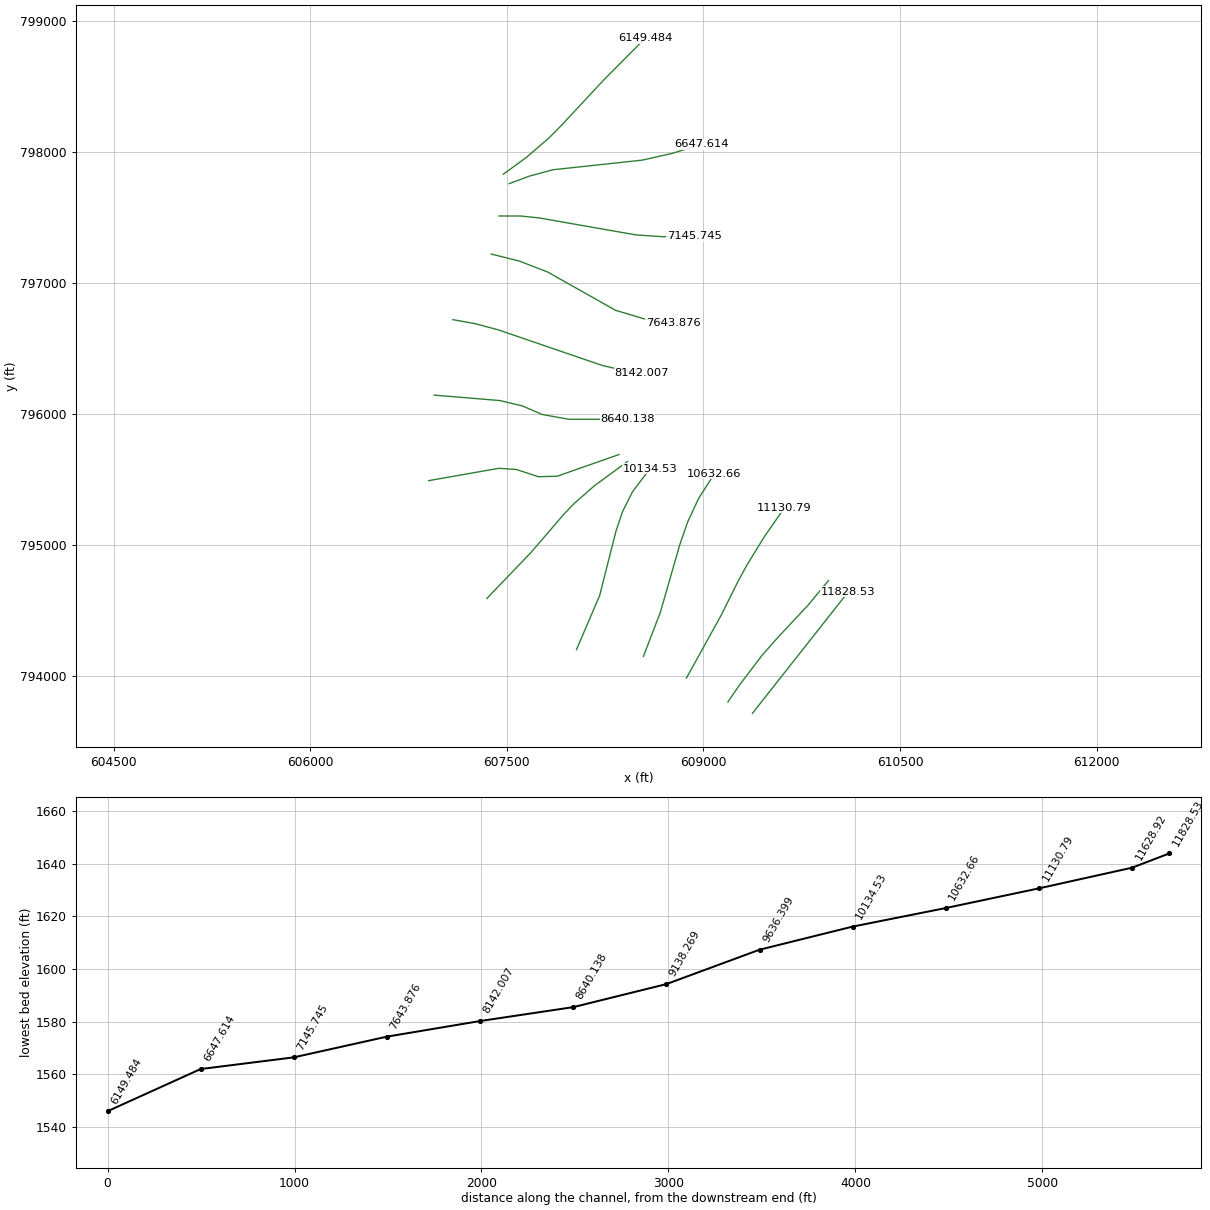
HEC-RAS study 10355_ras.prj: 10355

--- 10355_ras.g01 (geometry) --- (continued)

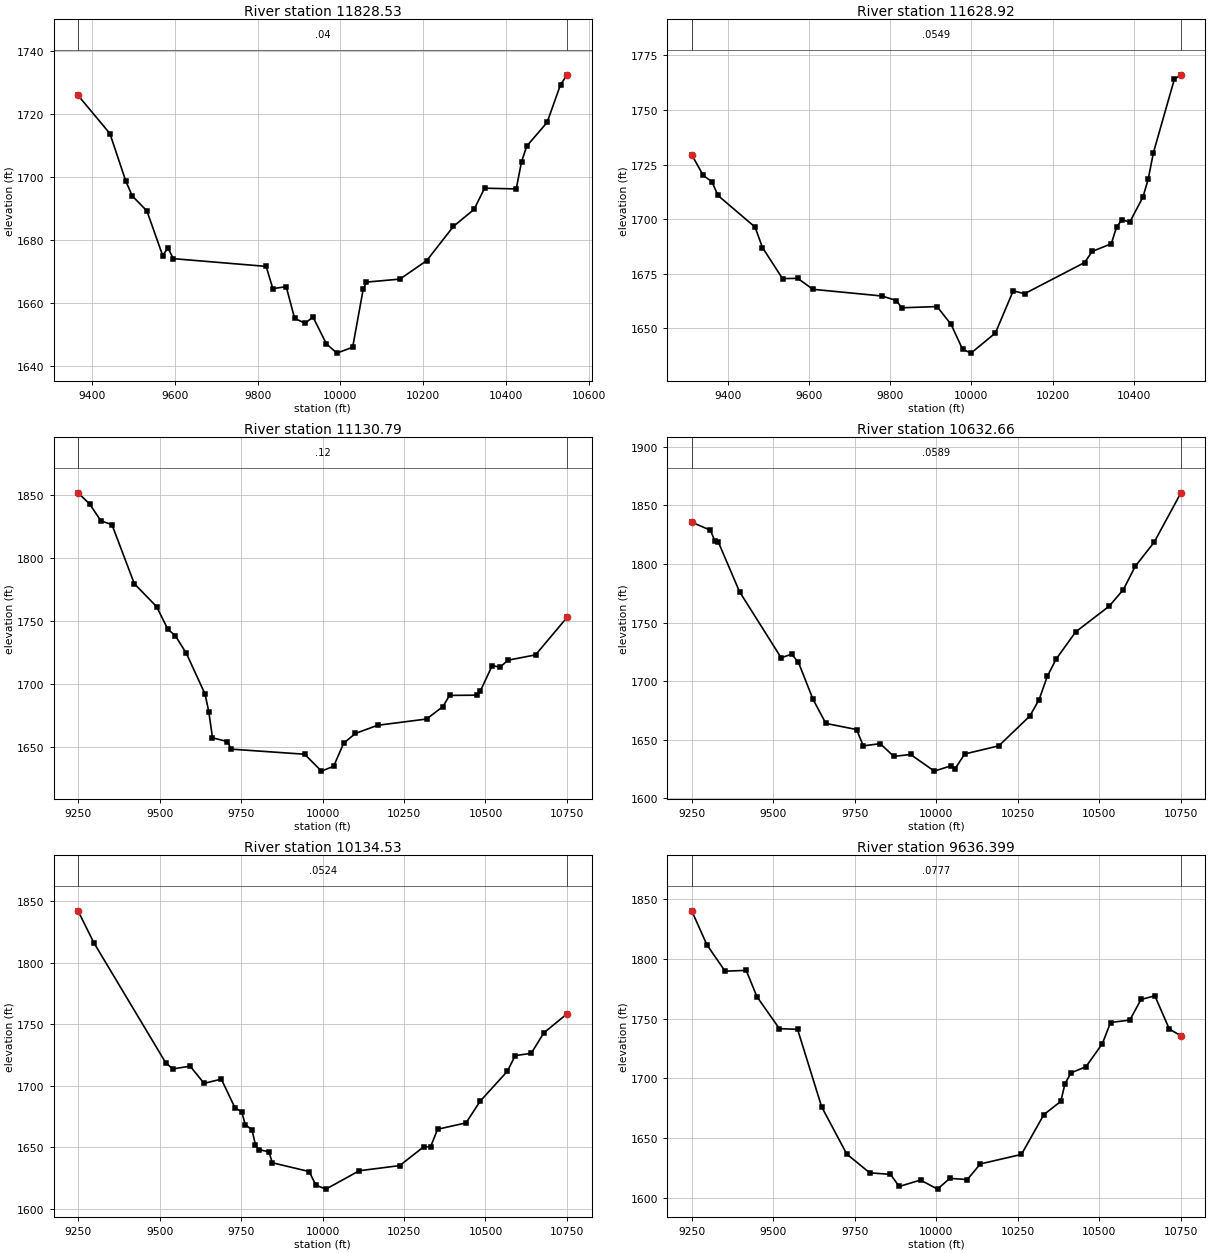
Type RM Length L Ch R = 1 ,11828.53,199.607100,199.607100,199.607100
XS GIS Cut Line= 2
609373.783260018793714.511173964610105.033260018794641.594507292
#Sta/Elev= 30
9366.5661726.0369443.6061713.8539481.8151698.7689497.7081693.9789532.7611689.262
 9570.97 1675.039583.7061677.5169596.4431674.0529820.653 1671.59  9836.81664.507
9869.0951665.1399889.3791655.0489914.8521653.4839933.6841655.4969965.9781646.965
 9991.271643.98310029.481645.86410054.951664.33110062.86 1666.59 10143.61667.543
10208.191673.42110272.781684.33310322.421689.71410347.891696.48110424.311696.247
10437.041704.90510449.781709.90210498.841717.41810531.131729.41410547.331732.559
#Mann= 3 , 0 , 0
9366.566    0.04       09366.566    0.04       010547.33    0.04       0
#XS Ineff= 2 , 0
       0                               0
Bank Sta=9366.566,10547.33
Exp/Cntr=0.3,0.1

Type RM Length L Ch R = 1 ,11628.92,498.130800,498.130800,498.130800
XS GIS Cut Line= 6
609186.896417384793801.709396798609275.147284261793930.511280225
 609446.45007348 794156.25389605609574.947523805794301.432868113
609797.416392347794538.518195115 609954.05654023794727.729508424
#Sta/Elev= 30
9311.5971729.501 9339.831720.0489361.3181717.1199376.1971710.8249467.4711696.336
9485.711 1686.95 9535.041672.7249572.5741672.8199609.8011667.8079779.7291664.743
9815.2611662.674 9828.411659.3359915.5251659.8969950.0811651.7129978.1871640.368
    99991638.54910059.121647.77510103.031667.121 10130.81665.78110278.771680.083
10297.411685.18610344.391688.67610357.521696.43310370.641699.62410390.05 1698.68
10422.491710.14210435.341718.39410448.181730.47910499.571764.06910515.921766.137
#Mann= 3 , 0 , 0
9311.597  0.0549       09311.597  0.0549       010515.92  0.0549       0
#XS Ineff= 2 , 0
       0                               0
Bank Sta=9311.597,10515.92
Exp/Cntr=0.3,0.1

Type RM Length L Ch R = 1 ,11130.79,498.130800,498.130800,498.130800
XS GIS Cut Line= 6
608870.337237983793983.657166583609134.150455438794460.729873448
609265.226424759794723.532508743609330.341486894794843.266873582
609463.190149538795059.669841134609618.669687265795283.855094015
#Sta/Elev= 30
9249.0091851.4899284.8251842.5999319.1061829.3489353.3871826.164 9421.951779.367
9490.5131761.1429524.7941743.2139547.6481738.235 9581.931724.0399639.0651691.788
9650.4921677.967 9661.921657.1179707.6281654.1619719.0551648.1439944.8521644.101
9996.4561630.69410033.811634.49810064.651652.84610100.921660.63310169.221667.079
10319.32 1672.0310369.481681.94810389.681690.77510472.581690.94410484.541694.375
10520.731714.43410544.861713.17510568.991718.69510653.811722.92410750.971752.811
#Mann= 3 , 0 , 0
9249.009    0.12       09249.009    0.12       010750.97    0.12       0
#XS Ineff= 2 , 0
       0                               0
Bank Sta=9249.009,10750.97
Exp/Cntr=0.3,0.1

Type RM Length L Ch R = 1 ,10632.66,498.130800,498.130800,498.130800
XS GIS Cut Line= 6
608542.456064092794149.523776926608671.016074702794484.228366817
608818.029649598 794995.65510153608879.588544388795173.877105045
608963.695116782795355.138899573609083.817878303795542.261693992
#Sta/Elev= 30
9249.0331835.5729306.3061828.815 9320.261819.4859331.138 1818.349395.7431776.314
9523.6711719.8859555.4921723.0149576.7051715.9639621.3581684.464 9660.791663.926
9754.886 1658.719775.7961644.7719827.7911646.6419869.2651635.7979921.108 1637.41
9993.6881623.21310045.651627.79910056.041624.69910087.231637.85710191.781644.794
   10287 1670.2310315.32 1684.1710340.591704.00810367.431718.693 10427.71741.993
10531.051764.06510574.16 1778.1410610.581797.92910668.591818.51710750.961860.678
#Mann= 3 , 0 , 0
9249.033  0.0589       09249.033  0.0589       010750.96  0.0589       0
#XS Ineff= 2 , 0
       0                               0
Bank Sta=9249.033,10750.96
Exp/Cntr=0.3,0.1

Type RM Length L Ch R = 1 ,10134.53,498.130800,498.130800,498.130800
XS GIS Cut Line= 6
608031.710542127794201.240884913 608208.27109003794612.974632213
608333.144132248795105.555860935608383.548936792795255.249674567
 608459.23915205 795405.51450718608591.075220562795579.562263326
#Sta/Elev= 30
9249.0381842.0829297.8981816.091 9517.991718.8899539.5521713.7389593.4591715.963
9636.0241702.0419689.0321705.444 9730.991682.1649751.9121678.8389762.3741668.546
9783.2961664.2359793.7121652.2599804.0671648.2219835.1331646.4819845.4891637.581
9958.6761630.4139979.227 1619.4210010.031616.15710112.531631.07210236.571635.257
10310.35 1650.4910331.651650.58110352.941664.76210440.371669.95810483.751687.549
10567.321711.86610591.311724.55610640.581726.38710678.951742.95910750.96 1758.58
#Mann= 3 , 0 , 0
9249.038  0.0524       09249.038  0.0524       010750.96  0.0524       0
#XS Ineff= 2 , 0
       0                               0
Bank Sta=9249.038,10750.96
Exp/Cntr=0.3,0.1

Type RM Length L Ch R = 1 ,9636.399,498.130800,498.130800,498.130800
XS GIS Cut Line= 6
607348.236062627794591.687884465607684.751015533794942.354731275
607933.489821991795231.643363053608008.845605679795311.331887461
608169.656207386795452.022444278608420.381912774795635.759861889
#Sta/Elev= 30
9249.0171840.1529295.553 1811.739351.432 1789.679416.2351790.334 9449.221768.299
9518.0041741.6149573.9581741.0069647.8291676.1939724.9551636.6899795.5371620.994
9859.1631619.7119885.9561609.5719951.3891614.96910003.521607.36710041.171616.393
10094.891615.354   101351628.43810261.161636.39510330.011669.69710382.021680.776
10395.011695.63610413.381704.59510459.331709.76710509.631729.06510534.781746.742
 10593.81748.75510628.431766.00510670.841769.05610714.991741.37910750.931735.529
#Mann= 3 , 0 , 0
9249.017  0.0777       09249.017  0.0777       010750.93  0.0777       0
#XS Ineff= 2 , 0
       0                               0
Bank Sta=9249.017,10750.93
Exp/Cntr=0.3,0.1

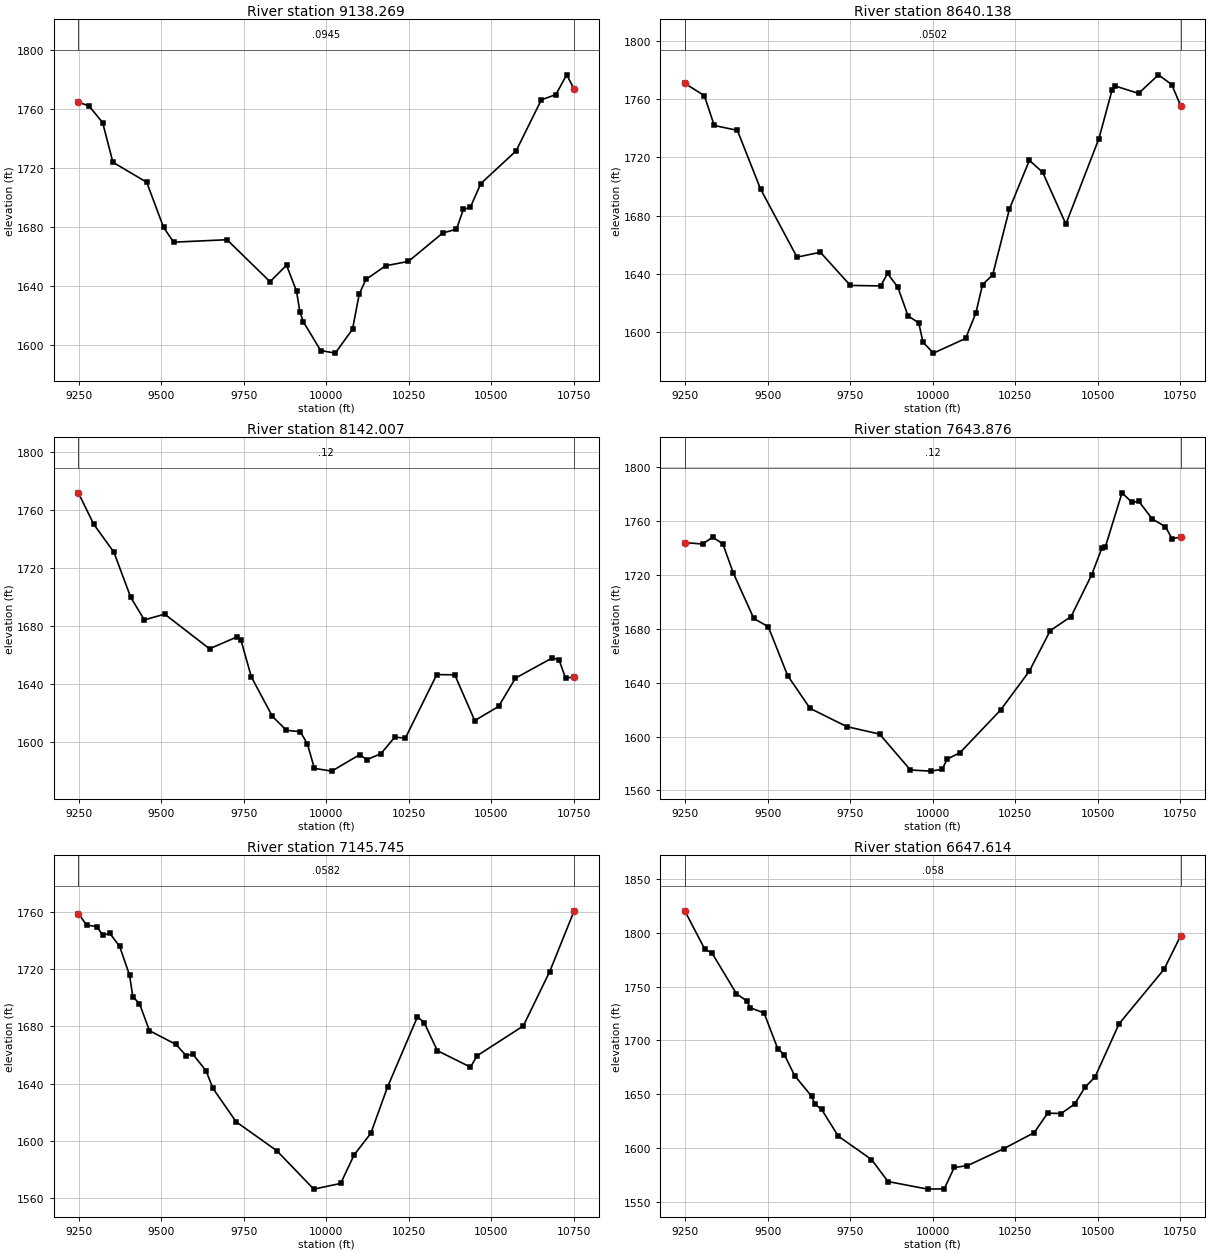
Type RM Length L Ch R = 1 ,9138.269,498.130800,498.130800,498.130800
XS GIS Cut Line= 6
606903.881498553795490.046647302607439.238741308 795584.20888821
607573.754492029795575.151101982607741.095817552795519.977129824
607883.347986636795523.638439368608355.700242181795689.044988304
#Sta/Elev= 30
 9249.131764.7859281.3531762.2459322.772 1750.899353.8361723.9599456.2561710.389
9507.245 1679.749537.8381669.672 9699.471671.3379829.7081642.8129879.7681653.999
9910.013 1636.449920.1531622.271 9930.331615.7169983.1081596.05210027.311594.292
10079.591610.52110099.891634.36610120.031644.33810180.121653.646 10248.8 1656.61
 10352.81675.89610394.451678.49910415.361691.93810436.27 1693.2810467.991709.441
10575.07 1731.7110651.541766.39210695.361769.93110728.221783.371 10750.91773.723
#Mann= 3 , 0 , 0
 9249.13  0.0945       0 9249.13  0.0945       0 10750.9  0.0945       0
#XS Ineff= 2 , 0
       0                               0
Bank Sta=9249.13,10750.9
Exp/Cntr=0.3,0.1

Type RM Length L Ch R = 1 ,8640.138,498.130800,498.130800,498.130800
XS GIS Cut Line= 6
606945.836944518796142.715382882607447.490072752796101.049106384
607617.777780119796060.405697246607771.961825944 795994.49619292
607972.916022892795958.392798912608421.773665047795958.335408628
#Sta/Elev= 30
9249.1211770.698 9308.291762.3199338.2921741.8149408.3371738.4599478.4691698.226
9589.0081651.4269659.6571654.7889750.6861631.9999842.5891631.6799863.1611640.233
9894.3261630.7979925.4921610.9999957.6221606.3679970.5351593.07410002.261585.537
10099.641595.61910130.53 1612.9610151.021632.634 10181.61639.22310232.191684.369
10292.84 1717.8910333.071709.65110403.381674.13310503.49 1732.84 10543.5 1766.35
 10553.51768.85410623.54 1763.83 10683.71776.58110723.911769.886 10750.91755.447
#Mann= 3 , 0 , 0
9249.121  0.0502       09249.121  0.0502       0 10750.9  0.0502       0
#XS Ineff= 2 , 0
       0                               0
Bank Sta=9249.121,10750.9
Exp/Cntr=0.3,0.1

Type RM Length L Ch R = 1 ,8142.007,498.130900,498.130900,498.130900
XS GIS Cut Line= 6
607088.721498206  796718.3129661607257.872508018796688.013349748
607434.832686595796640.574225749 608225.58393886796369.897666334
608366.879100103796335.989233506608530.721341377796312.743433218
#Sta/Elev= 30
9249.0351771.7989295.7781750.1499356.8721730.874 9407.81 1699.839448.8881684.351
9510.7361688.2889646.4621664.4579730.7051672.7359741.2361670.771 9772.991645.152
9836.7161618.0079879.1991608.3689921.6831607.3659942.9251598.9639964.0341582.153
10016.771580.25310101.48 1591.6310122.731588.12710165.22 1592.1810207.721603.643
10239.591602.96510334.72 1646.6810389.261646.55410449.791615.03710522.031624.746
10573.261644.28610684.831658.18610705.031656.91810725.131644.13810750.971645.237
#Mann= 3 , 0 , 0
9249.035    0.12       09249.035    0.12       010750.97    0.12       0
#XS Ineff= 2 , 0
       0                               0
Bank Sta=9249.035,10750.97
Exp/Cntr=0.3,0.1

Type RM Length L Ch R = 1 ,7643.876,498.130800,498.130800,498.130800
XS GIS Cut Line= 6
607382.247803871797218.572364692607594.306667645797165.860591242
607810.115209528 797082.68644953 608329.60407012796789.769626824
608548.523068487796724.201650884608770.843332519796692.391204834
#Sta/Elev= 30
9249.083 1744.149302.7931743.0069333.5691748.195 9364.461743.0779395.6681721.662
9458.085 1687.749501.938 1681.61 9560.53 1645.329628.477 1620.959740.0431607.349
9838.9931601.8459932.4561575.168 9994.011574.32110028.531575.68310044.141583.331
10082.721588.02610205.321619.67210292.381648.47610356.051678.74510419.131689.168
10481.411720.15610512.23 1739.9210522.621740.74510573.351781.07210603.841773.893
10624.171774.80110664.591761.69310704.881755.89510724.951746.93410750.881748.197
#Mann= 3 , 0 , 0
9249.083    0.12       09249.083    0.12       010750.88    0.12       0
#XS Ineff= 2 , 0
       0                               0
Bank Sta=9249.083,10750.88
Exp/Cntr=0.3,0.1

Type RM Length L Ch R = 1 ,7145.745,498.130800,498.130800,498.130800
XS GIS Cut Line= 6
607439.972999237797509.302418268607605.429944219797509.205342469
607749.931887404797493.957915706608484.895563215797365.023235341
608691.946568337797351.162586201608928.840468924797355.623883919
#Sta/Elev= 30
 9249.021758.6619274.0821750.7039304.1061749.5999324.1061743.5279344.1061744.995
9374.1221735.8519404.1491715.7199414.1581700.5859434.2191695.9329464.3121677.017
 9544.881667.3979575.2061659.6429595.4941660.688 9636.071648.9679656.3591636.891
9727.0931613.3979850.0011593.2779962.2581566.443 10043.71570.41510084.351590.278
10134.961605.40610185.571637.65110276.281686.69910296.431682.69210336.621663.057
 10436.91651.57510456.921659.509   105971680.32210677.031718.28510750.971760.621
#Mann= 3 , 0 , 0
 9249.02  0.0582       0 9249.02  0.0582       010750.97  0.0582       0
#XS Ineff= 2 , 0
       0                               0
Bank Sta=9249.02,10750.97
Exp/Cntr=0.3,0.1

Type RM Length L Ch R = 1 ,6647.614,498.130800,498.130800,498.130800
XS GIS Cut Line= 6
607518.504312218797756.230717853607673.689201886797813.831527265
607852.479710078797862.023363881608533.851883987797935.549938815
608762.980506924797987.221969837608982.531743731798056.302791957
#Sta/Elev= 30
9249.0531820.3849309.6281784.7519331.0721781.3799405.4251743.4619436.8371736.679
9447.2671730.3859489.1381725.5939530.4911692.4849551.0481686.5539581.8841667.335
9632.9361648.318 9643.111640.9569663.4571635.9619713.9691611.2159814.5551589.504
9864.6561569.0449984.8391562.00610035.051562.29110065.171582.11310105.321583.795
10216.111599.69910307.371614.45610348.171632.54810388.981632.20110430.071640.959
10460.991656.49310491.911666.221 10564.51715.48310700.861766.15210750.951797.116
#Mann= 3 , 0 , 0
9249.053   0.058       09249.053   0.058       010750.95   0.058       0
#XS Ineff= 2 , 0
       0                               0
Bank Sta=9249.053,10750.95
Exp/Cntr=0.3,0.1

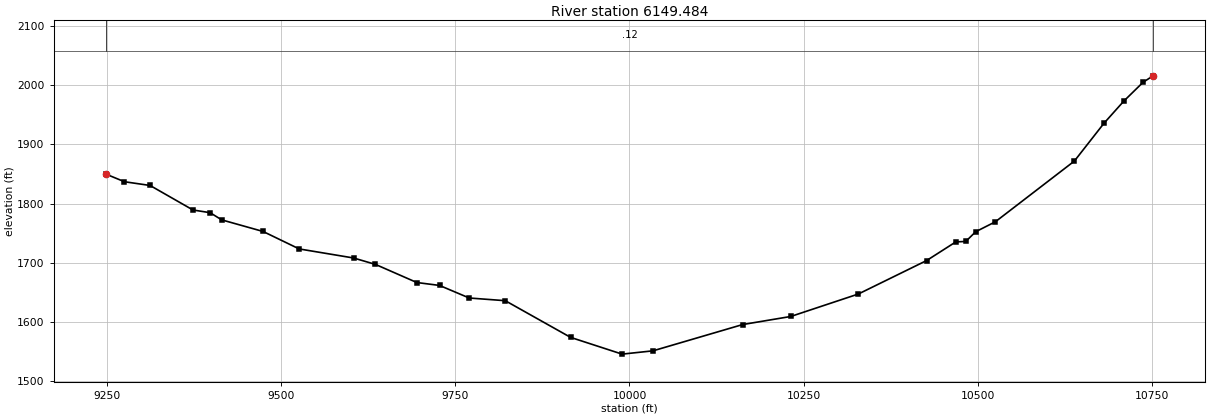
Type RM Length L Ch R = 1 ,6149.484,498.130800,498.130800,498.130800
XS GIS Cut Line= 6
607473.210866962797827.807381305 607649.83964362797956.703639475
607824.989829058798107.781639615607916.905065749798200.564662733
608234.809940386798542.318302103608555.245258888 798864.65297627
#Sta/Elev= 30
9249.0461849.8139275.6951836.9399312.3871830.6499373.9651789.2349398.5181784.708
9415.1161772.5939474.4291753.0069526.3131723.5079604.3291708.2229635.6661697.409
9694.9851666.8289727.5431661.919 9770.171640.693 9821.881636.1429915.5511574.244
9989.429 1545.9610033.741551.52210162.411595.90310231.291609.49610328.261647.419
10426.331703.98910468.081735.38610482.361736.15810496.511752.48910524.841769.376
10638.161871.86210680.661935.72410708.991972.97810736.532004.66610750.992015.702
#Mann= 3 , 0 , 0
9249.046    0.12       09249.046    0.12       010750.99    0.12       0
#XS Ineff= 2 , 0
       0                               0
Bank Sta=9249.046,10750.99
Exp/Cntr=0.3,0.1