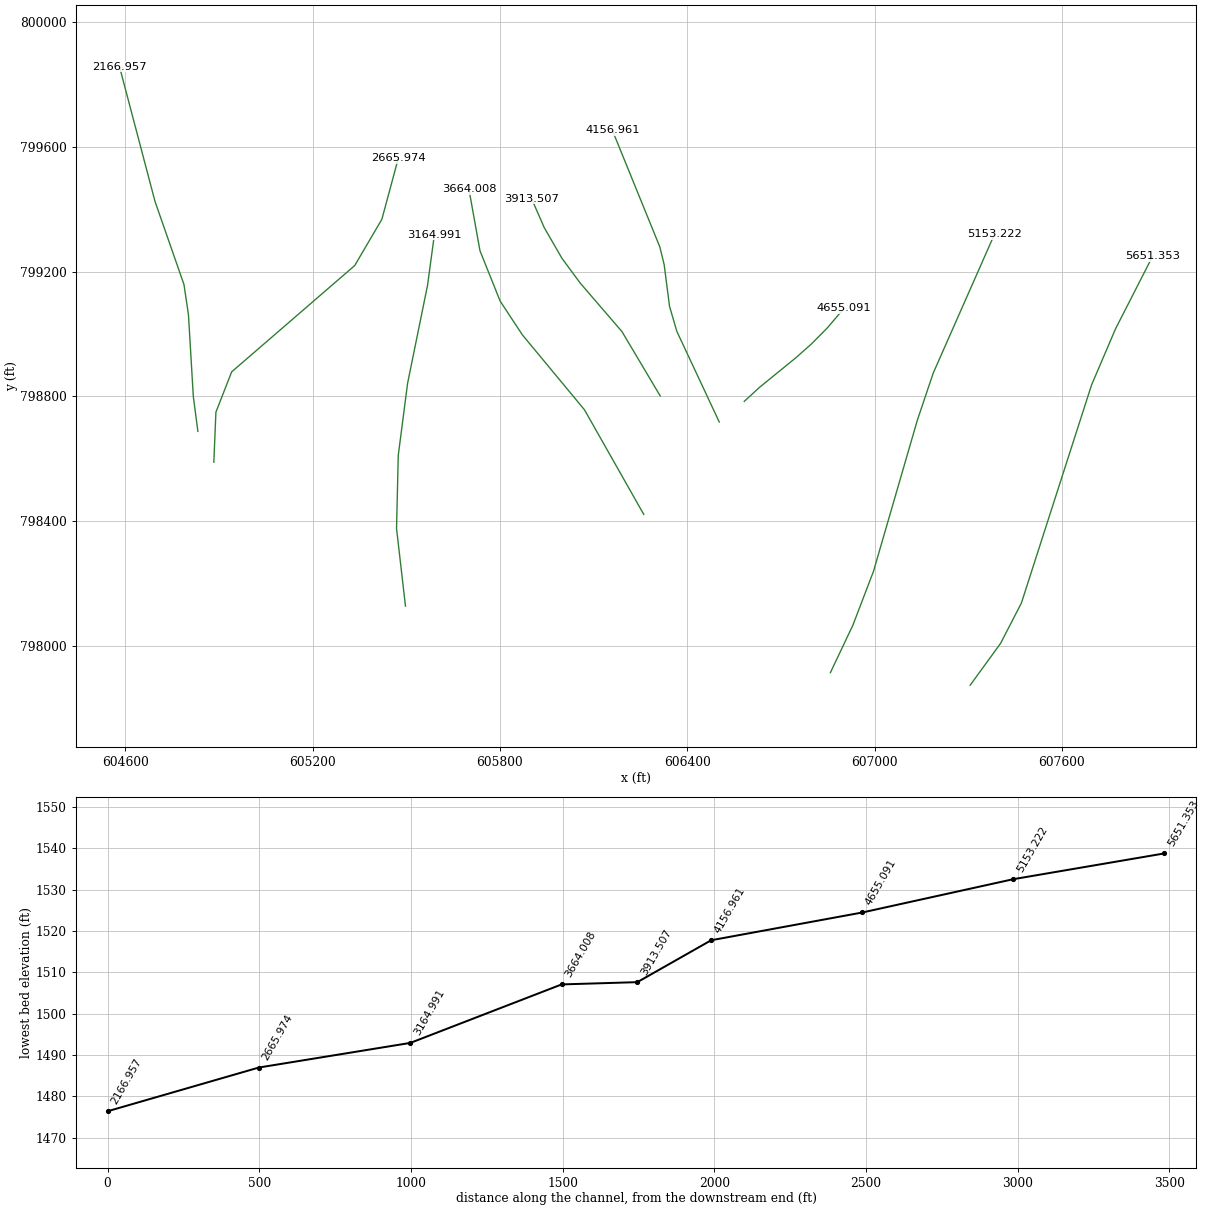
HEC-RAS study 10355_ras.prj: 10355

--- 10355_ras.g01 (geometry) --- (continued)

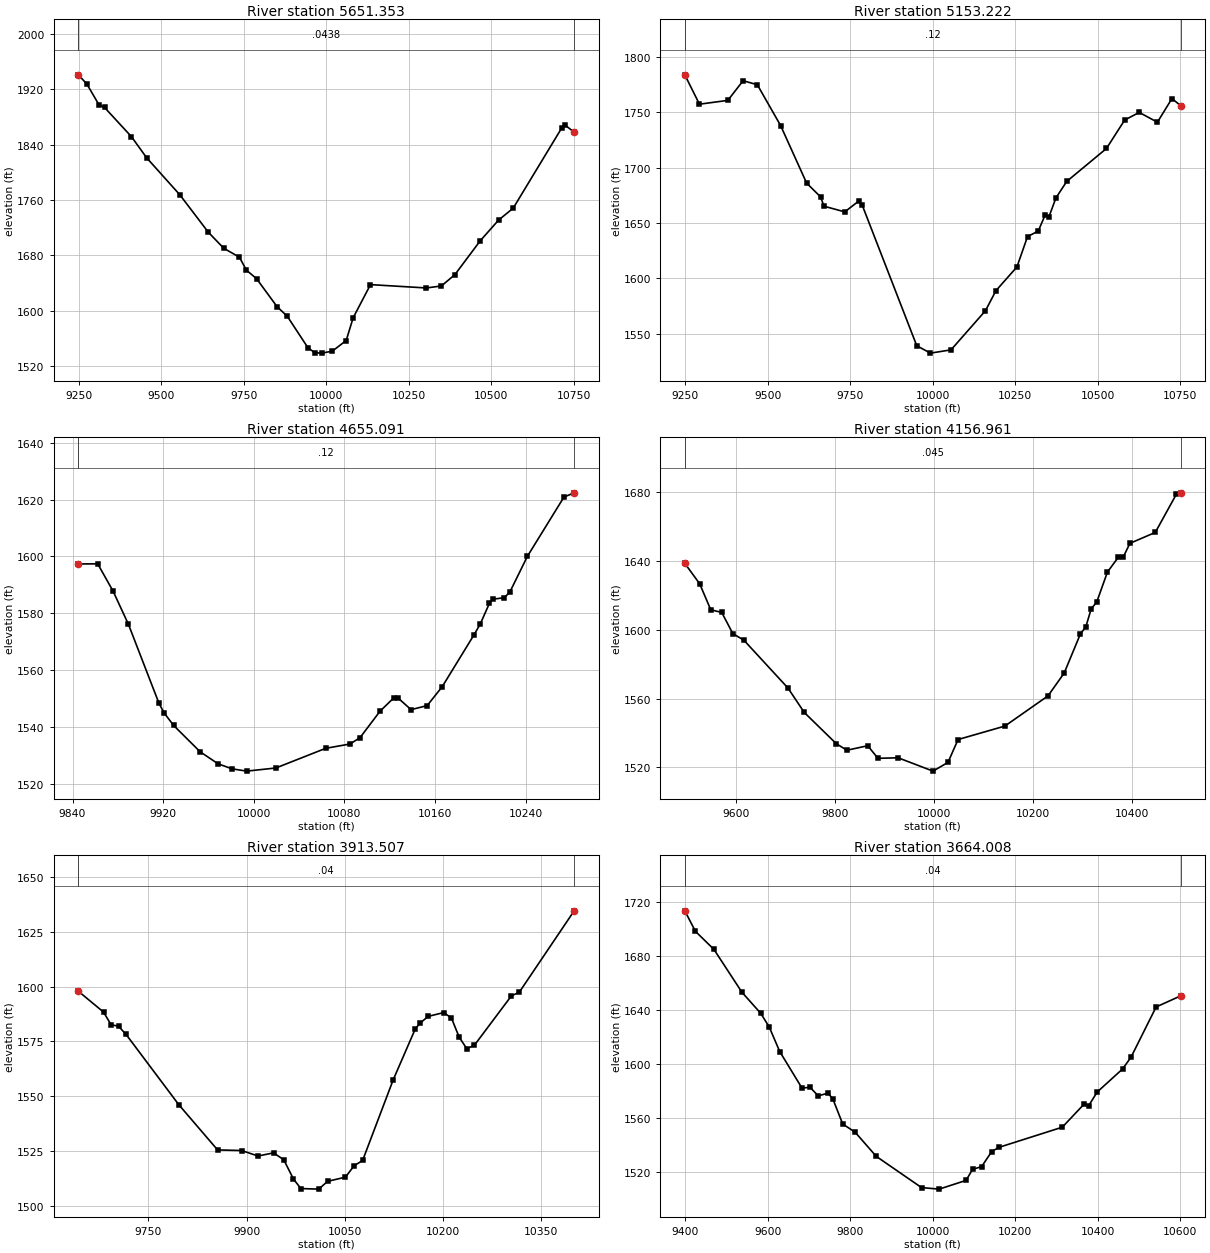
Type RM Length L Ch R = 1 ,5651.353,498.130800,498.130800,498.130800
XS GIS Cut Line= 6
607305.977793012797875.180742951 607403.22319472798008.961109532
607469.892529581798137.993519284607694.730670702798836.773888226
607771.510631507799016.550387869607890.196819018799248.816257224
#Sta/Elev= 30
9249.0531940.7179274.8441927.4529311.5051897.5049328.3991893.614  9409.91851.408
9456.1661820.7969556.6121767.3979642.648 1713.46 9689.591690.2299737.0911677.298
9757.9141658.7219789.0241646.2429850.9871605.9399881.968 1592.02 9944.181546.868
9964.9961539.3839986.1741538.79410018.131541.57910060.431557.01210081.451589.783
10134.011637.72610303.451632.90410348.781635.78910389.851652.239 10466.51701.061
10521.811730.828 10566.41748.19810712.661863.46410723.991868.01510750.961857.763
#Mann= 3 , 0 , 0
9249.053  0.0438       09249.053  0.0438       010750.96  0.0438       0
#XS Ineff= 2 , 0
       0                               0
Bank Sta=9249.053,10750.96
Exp/Cntr=0.3,0.1

Type RM Length L Ch R = 1 ,5153.222,498.130800,498.130800,498.130800
XS GIS Cut Line= 6
606858.247818338797915.222681406606930.316322685798067.240571282
606996.202196813798239.426474137607136.764979695798723.751645839
607187.787956895798875.099266348607383.594732033799318.806962367
#Sta/Elev= 30
9249.0361783.7369293.3681757.2389379.324 1760.669425.6651778.4199468.7591774.783
9539.2431737.9619618.0851686.0169660.1851673.623 9670.711665.1699733.5931660.046
9775.3561669.6749785.7971666.6389951.7091539.204 9993.17 1532.5610055.461535.514
10159.891570.88410191.44  1588.910255.121610.35510287.251637.79410319.521642.658
10341.031657.54410351.781655.35310373.291672.66110405.95 1687.5210526.331717.271
10581.441742.89710625.531749.82510680.641740.96110724.731762.32610750.971755.909
#Mann= 3 , 0 , 0
9249.036    0.12       09249.036    0.12       010750.97    0.12       0
#XS Ineff= 2 , 0
       0                               0
Bank Sta=9249.036,10750.97
Exp/Cntr=0.3,0.1

Type RM Length L Ch R = 1 ,4655.091,498.130800,498.130800,498.130800
XS GIS Cut Line= 6
606582.404976548798784.072990131606631.757194457798829.405577032
606746.718600392798922.931748825606796.894711059798967.269958741
606847.993914018 799018.85298952 606901.81423455799081.855402505
#Sta/Elev= 30
9845.1211597.3469862.2231597.3919875.8011587.7819889.3791576.0869916.318 1548.33
9920.9841544.8859929.2221540.5739952.6261531.3039968.4481527.0789980.8411525.301
9993.746  1524.510019.491525.60810063.461532.51910084.731534.02310093.661536.212
10111.421545.57210123.861550.37910127.291550.21810138.811546.11710153.021547.539
10166.331554.21410194.481572.499 10199.91576.24910207.991583.53210210.691584.932
10221.141585.48810226.081587.54110241.481600.02710273.751620.86610282.76 1622.36
#Mann= 3 , 0 , 0
9845.121    0.12       09845.121    0.12       010282.76    0.12       0
#XS Ineff= 2 , 0
       0                               0
Bank Sta=9845.121,10282.76
Exp/Cntr=0.3,0.1

Type RM Length L Ch R = 1 ,4156.961,243.453200,243.453200,243.453200
XS GIS Cut Line= 6
 606502.48020775798718.026664081 606366.72645695799008.026707512
606343.164336532 799088.69726117606326.022584433799221.871809271
606312.285052129799278.337736935606159.703329964799653.294641286
#Sta/Elev= 30
9496.4591638.6419526.545 1626.759548.8531611.6579571.1611610.0719593.4691597.791
9615.7761593.9619704.8951566.1329737.7761551.9439802.8031533.6759824.1581529.943
9866.1351532.5649886.7721525.237 9927.591525.5439998.0391517.788 10028.31522.867
10048.621536.16810143.291543.99610230.46 1561.5710263.191574.90610295.921597.632
10306.831601.71810317.741612.25810328.651615.98910350.481633.57410372.191642.073
10382.911642.54410395.871650.27710447.151656.61310489.571678.73810498.371679.652
#Mann= 3 , 0 , 0
9496.459   0.045       09496.459   0.045       010498.37   0.045       0
#XS Ineff= 2 , 0
       0                               0
Bank Sta=9496.459,10498.37
Exp/Cntr=0.3,0.1

Type RM Length L Ch R = 1 ,3913.507,249.499700,249.499700,249.499700
XS GIS Cut Line= 6
606313.453769909798801.428981339606190.760230161799007.723360276
606057.541851685 799162.47406584605998.715070411799242.199604734
605942.021714151799340.423583842605901.578288631799432.742750748
#Sta/Elev= 30
9642.7561597.8789681.2841588.359 9692.761582.6319704.2371581.8949715.7141578.185
9796.441 1546.099855.6131525.5239892.2721525.2539917.4261522.7489941.1671524.179
9956.7381521.0489971.5581512.2569982.9351507.90510010.151507.65110023.821511.204
10050.961513.10910064.16 1518.2410077.351520.75910123.981557.45210157.811580.727
10165.381583.40810177.561586.40310201.361588.15310213.091585.62210224.831576.956
10236.56 1571.6310248.281573.30210304.831595.81410316.561597.33810400.621634.525
#Mann= 3 , 0 , 0
9642.756    0.04       09642.756    0.04       010400.62    0.04       0
#XS Ineff= 2 , 0
       0                               0
Bank Sta=9642.756,10400.62
Exp/Cntr=0.3,0.1

Type RM Length L Ch R = 1 ,3664.008,499.016700,499.016700,499.016700
XS GIS Cut Line= 6
606260.673781497  798422.1048608606070.815035063798757.143855387
605871.954463078798997.101173364605800.708766633799105.409852094
 605736.17267706799266.407827046605700.681536382799463.879382301
#Sta/Elev= 30
9399.0411713.7769424.7921698.5529469.7821685.078 9537.511653.3059583.056 1637.69
9603.7571627.4739629.1341609.2729683.2861582.0489702.3371582.8179722.4951576.355
9746.2321578.413  9758.11573.9239781.8361555.4379811.8351549.405 9863.061531.452
9972.8191508.256 10015.51507.10510080.821513.59210096.541521.79510118.451523.796
10142.941534.97810160.591538.138 10314.11553.10610367.311570.38210377.751568.929
10398.611579.19610460.16 1596.3310480.671605.09310541.491642.38810600.881650.604
#Mann= 3 , 0 , 0
9399.041    0.04       09399.041    0.04       010600.88    0.04       0
#XS Ineff= 2 , 0
       0                               0
Bank Sta=9399.041,10600.88
Exp/Cntr=0.3,0.1

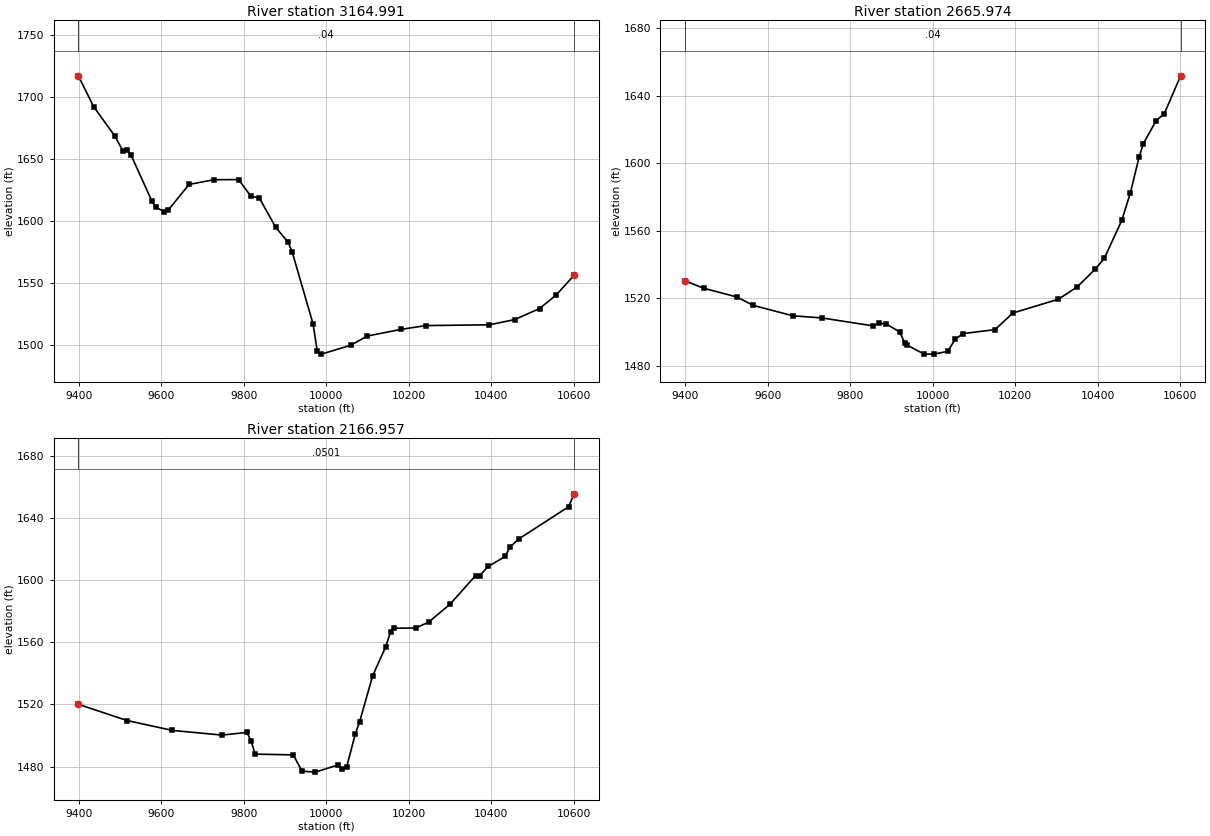
Type RM Length L Ch R = 1 ,3164.991,499.016700,499.016700,499.016700
XS GIS Cut Line= 6
605497.579090348798128.439493485 605468.94314592798376.953374714
605474.505667486798611.544474478605504.342456851 798841.93324015
605568.325954112799156.279396393605590.181034287799318.314807053
#Sta/Elev= 30
9399.081 1717.089436.1381692.298 9486.791668.9289506.9461656.8159517.0241657.116
9527.1031653.0719577.2671616.2619587.2961611.1749607.3541607.7489617.3831609.124
9667.4771629.6199727.4791633.3749787.519 1633.55 9817.561620.0439837.5881618.842
9877.6441594.9919907.7651583.0319917.8131574.8089968.0531517.2889978.162 1495.55
9988.3071492.95410059.171500.08810099.531507.50710180.761512.85810242.111515.958
10395.43 1516.5510456.381520.75610517.091529.63710557.36 1540.5910600.97  1556.5
#Mann= 3 , 0 , 0
9399.081    0.04       09399.081    0.04       010600.97    0.04       0
#XS Ineff= 2 , 0
       0                               0
Bank Sta=9399.081,10600.97
Exp/Cntr=0.3,0.1

Type RM Length L Ch R = 1 ,2665.974,499.016800,499.016800,499.016800
XS GIS Cut Line= 6
604883.851304348798589.493187717604890.539269091798749.665283001
604940.980395157798878.684799073605334.898414932799218.929551686
 605421.92263405799367.063087723605474.984303798799563.725459348
#Sta/Elev= 30
9399.0651530.5069444.6411526.052 9524.881520.8869565.4591515.8359660.8871509.725
9730.8811508.4529854.7531503.7829870.5541505.1929886.5971504.9819919.7531500.171
9931.8981493.8169938.8151492.2469979.0041487.02310001.961487.004 10036.7 1488.65
10054.211495.79710073.311499.163 10151.11501.52110194.111511.35810304.84 1519.55
10350.341526.863 10394.51537.53310415.941543.758 10458.31566.28710479.281582.677
10499.961603.528 10510.3 1611.5710541.061625.15210561.431629.54310600.891651.878
#Mann= 3 , 0 , 0
9399.065    0.04       09399.065    0.04       010600.89    0.04       0
#XS Ineff= 2 , 0
       0                               0
Bank Sta=9399.065,10600.89
Exp/Cntr=0.3,0.1

Type RM Length L Ch R = 1 ,2166.957,0.000000,0.000000,0.000000
XS GIS Cut Line= 6
604832.786081636798687.999585298604818.176816167798799.471569935
 604802.61946612799061.201855167604788.277947531799158.232707227
604695.571025218799424.098082582604581.614893203 799856.51474859
#Sta/Elev= 30
9399.0771520.0999517.0651509.6659627.2591503.2649747.4711500.2769807.7721501.996
9817.8481496.3059827.9241488.0229920.2151487.5219941.182 1477.039973.5671476.426
10027.611480.97610038.421478.42610049.231479.51510070.471500.969   100811508.939
 10112.61538.47610144.191557.153 10155.91566.69310165.091569.04510216.981569.231
10248.121572.99910299.911584.48310361.881602.919 10372.21602.99210392.861608.901
10434.171615.28110444.491621.09110467.28 1626.6410587.411647.25910600.971655.604
#Mann= 3 , 0 , 0
9399.077  0.0501       09399.077  0.0501       010600.97  0.0501       0
#XS Ineff= 2 , 0
       0                               0
Bank Sta=9399.077,10600.97
Exp/Cntr=0.3,0.1